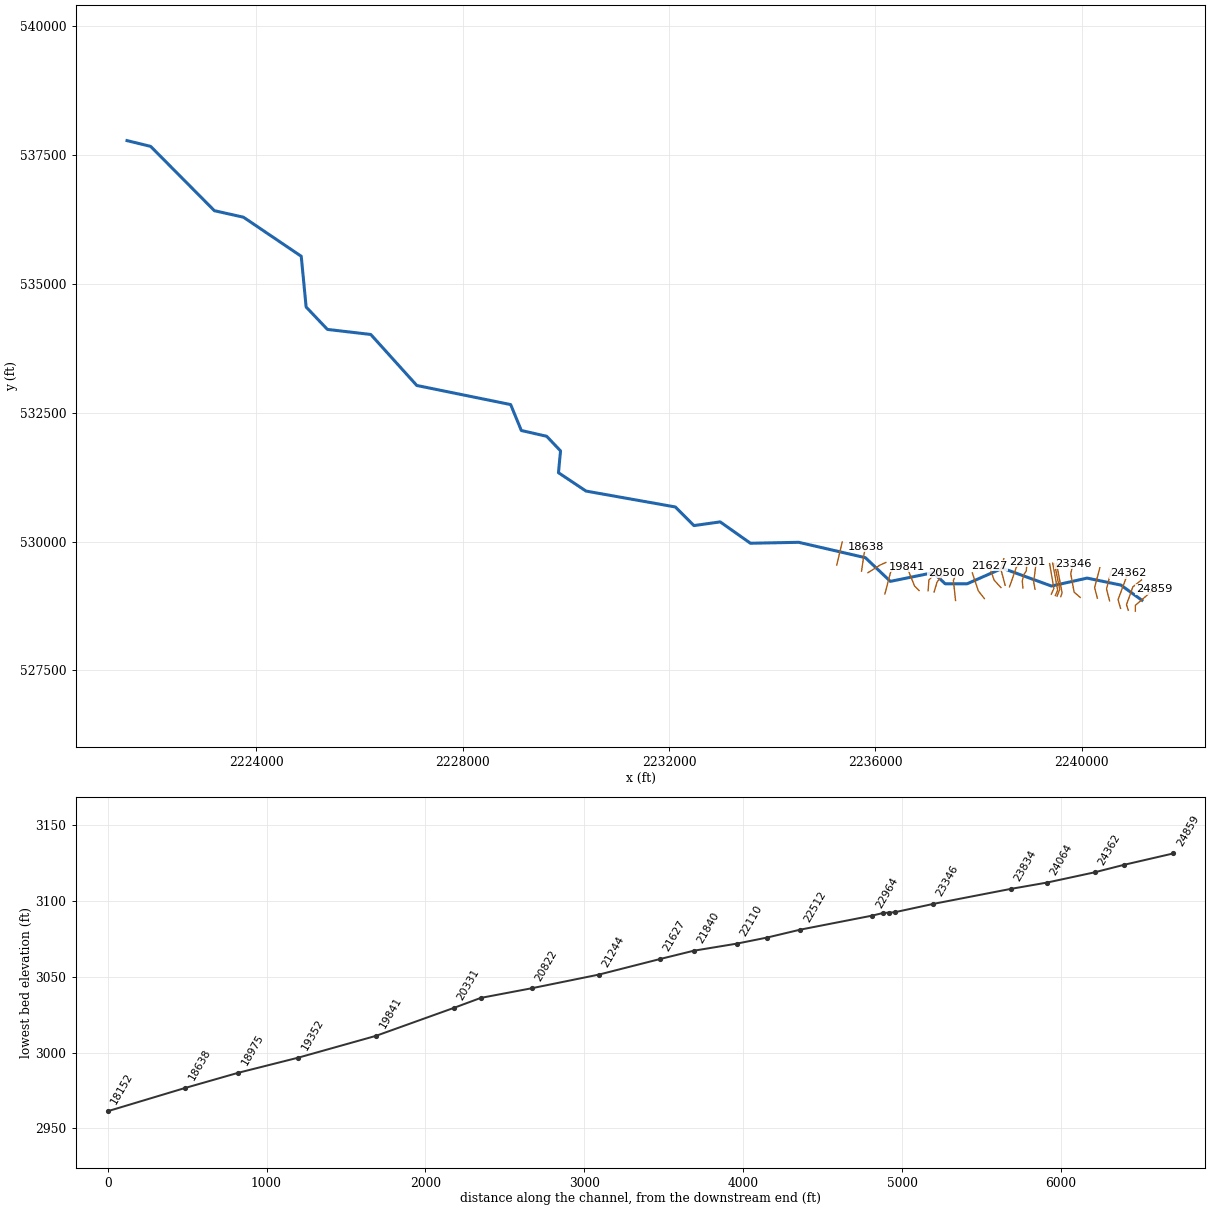
--- DRYFK.prj (project) ---

Proj Title=DRYFK
Current Plan=p01
Default Exp/Contr=0,0
English Units
Geom File=g01
Flow File=f01
Plan File=p01
BEGIN DESCRIPTION:
----------MODEL BY WOOD PLC 2021----------
Stream Name: Dry Fork
Flood Zone: Approximate
Pocahontas County, WV
HEC-RAS Version: RAS 6.1
Vertical Datum: NAVD88
Projection: NAD 1983 StatePlane West Virginia S FIPS 4702 (US Feet)
Terrain: 1-meter LIDAR (FEMA Region III 3DEP collected 2016-2018)
Land Use: 2019 NLCD
Hydrologic Method:
WV SIR2010-5033 regression equations
Model Notes:
KWSE tie in to Randolph County.
END DESCRIPTION:
DSS Export Rating Curves= 0
DSS Export Rating Curve Sorted= 0
DSS Export Volume Flow Curves= 0
DXF OffsetX= 0
DXF OffsetY= 0
DXF ScaleX= 0
DXF ScaleY= 0

--- DRYFK.p01 (plan) ---

Plan Title=Floodplain
Program Version=6.10
Short Identifier=Floodplain
Geom File=g01
Flow File=f01
Subcritical Flow
K Sum by GR= 0
Std Step Tol= 0.01
Critical Tol= 0.01
Num of Std Step Trials= 20
Max Error Tol= 0.3
Flow Tol Ratio= 0.001
Split Flow NTrial= 30
Split Flow Tol= 0.02
Split Flow Ratio= 0.02
Log Output Level= 0
Friction Slope Method= 1
Unsteady Friction Slope Method= 2
Unsteady Bridges Friction Slope Method= 1
Parabolic Critical Depth
Global Vel Dist= 0 , 0 , 0
Global Log Level= 0
CheckData=True
Encroach Param=-1 ,0,0, 0
Mapping Interval=1HOUR
Computation Time Step Use Courant=        0
Computation Time Step Use Time Series=    0
Computation Time Step Count To Double=0
Computation Time Step Max Doubling=0
Computation Time Step Max Halving=0
Computation Time Step Residence Courant=0
Run HTab= 0
Run UNet= 0
Run Sediment= 0
Run PostProcess= 0
Run WQNet= 0
Run RASMapper=-1
UNET Theta= 0
UNET Theta Warmup= 0
UNET ZTol= 0
UNET ZSATol= 0
UNET MxIter= 0
UNET Max Iter WO Improvement= 0
UNET MaxInSteps= 0
UNET DtIC= 0
UNET DtMin= 0
UNET MaxCRTS= 0
UNET WFStab= 0
UNET SFStab= 0
UNET WFX= 1
UNET SFX= 1
UNET Gravity=32.174
UNET 1D Methodology=Finite Difference
UNET DSS MLevel= 1
UNET Pardiso=0
UNET DZMax Abort= 0
UNET Use Existing IB Tables= 0
UNET Froude Reduction=False
UNET Froude Limit= 0
UNET Froude Power= 0
UNET D1 Cores= 0
UNET WindReference=Eulerian
UNET WindDragFormulation=Hsu (1988)
UNET D2 Coriolis=0
UNET D2 Cores= 0
UNET D2 Theta= 1
UNET D2 Theta Warmup= 1
UNET D2 Z Tol= 0.01
UNET D2 Volume Tol= 0.01
UNET D2 Max Iterations= 20
UNET D2 Equation= 0
UNET D2 RampUpFraction=0.1
UNET D2 TimeSlices= 1
UNET D2 Turbulence Formulation=Non-Conservative (original)
UNET D2 Eddy Viscosity=0.3
UNET D2 Transverse Eddy Viscosity=0.1
UNET D2 Smagorinsky Mixing=0
UNET D2 BCVolumeCheck=0
UNET D2 Cores=0
UNET D2 SolverType=PARDISO (Direct)
UNET D2 Minimum Iterations= 2147483647
UNET D2 Maximum Iterations= 2147483647
UNET D2 Restart Number= 10
UNET D2 Relaxation Coeff=1.3
UNET D2 SOR Precondition Iterations= 10
UNET D2 ILUT Maximum Fill= 8
UNET D2 ILUT Tolerance=1E-08
UNET D1D2 MaxIter= 0
UNET D1D2 ZTol=0.01
UNET D1D2 QTol=0.1
UNET D1D2 MinQTol=1
Write IC File= 0
Write IC File at Fixed DateTime=0
Write IC File at Sim End=0
Echo Input=False
Echo Parameters=False
Echo Output=False
Write Detailed= 0
HDF Write Warmup=0
HDF Write Time Slices=0
HDF Flush=0
HDF Compression= 1
HDF Chunk Size= 1
HDF Spatial Parts= 1
HDF Use Max Rows=0
HDF Fixed Rows= 1
Calibration Method= 0
Calibration Iterations= 20
Calibration Max Change=0.05
Calibration Tolerance=0.2
Calibration Maximum=1.5
Calibration Minimum=0.5
Calibration Optimization Method= 1
WQ AD Non Conservative
WQ ULTIMATE=-1
WQ Max Comp Step=1HOUR
WQ Output Interval=15MIN
WQ Output Selected Increments= 0
WQ Output face flow=0
WQ Output face velocity=0
WQ Output face area=0
WQ Output face dispersion=0
WQ Output cell volume=0
WQ Output cell surface area=0
WQ Output cell continuity=0
WQ Output cumulative cell continuity=0
WQ Output face conc=0
WQ Output face dconc_dx=0
WQ Output face courant=0
WQ Output face peclet=0
WQ Output face adv mass=0
WQ Output face disp mass=0
WQ Output cell mass=0
WQ Output cell source sink temp=0
WQ Output nsm pathways=0
WQ Output nsm derived pathways=0
WQ Create Restart=0
WQ Fixed Restart=0
WQ System Summary=0
WQ Write To DSS=0
Sorting and Armoring Iterations= 10
XS Update Threshold= 0.02
Bed Roughness Predictor= 0
Hydraulics Update Threshold= 0.02
Energy Slope Method= 1
Volume Change Method= 1
Sediment Retention Method= 0
Sediment TS Multiplier= 1
Warm Up Method= 0
XS Weighting Method= 0
Number of US Weighted Cross Sections= 1
Number of DS Weighted Cross Sections= 1
Upstream XS Weight=0
Main XS Weight=1
Downstream XS Weight=0
Number of DS XS's Weighted with US Boundary= 1
Upstream Boundary Weight= 1
Weight of XSs Associated with US Boundary= 0
Number of US XS's Weighted with DS Boundary= 1
Downstream Boundary Weight= 0.5
Weight of XSs Associated with DS Boundary= 0.5
Percentile Method= 0
Sediment Output Level= 3
Mass or Volume Output= 0
Output Increment Type= 1
Profile and TS Output Increment= 1
Transport Output Increment 1
XS Output Flag= 0
XS Output Increment= 10
Read HDF5 Sediment Hotstart= 0
Sediment Hotstart Type= 0
Write Gradation File= 0
Read Gradation Hotstart= 0
Write HDF5 File= 1
Write Binary Output= 1
Write DSS Sediment File= 0
DSS Sediment Output Type= 1
SV Curve= 0
Specific Gage Flag= 0
Subcell Erosion Methods= 0
Subcell Deposition Methods= 0
Advection Scheme= 1
Matrix Solver= 0
Implicit Weighting Factor= 1
Maximum Outer Loop Convergence Iterations= 5
Convergence Maximum Absolute= 0.001
Convergence RMSE= 0.0001
Grain Fractions Max Abs Error= 0.001
Max Subgrid Regions= 1
Max Subgrid Length Scale= 3.402823E+38
Initial Layer Thickness= 3.402823E+38
Min Layer Thickness= 3.402823E+38
Max Layer Thickness= 3.402823E+38
Number of Layers= 5

--- DRYFK.f01 (steady flow) ---

Flow Title=Flow
Program Version=6.10
Number of Profiles= 6
Profile Names=01pct,10pct,04pct,02pct,0_2pct,01plus
River Rch & RM=DRYFK,Main            ,24859
     586     310     412     497     819     867
River Rch & RM=DRYFK,Main            ,22512
     653     347     460     553     910     965
River Rch & RM=DRYFK,Main            ,20331
     732     391     517     621    1020    1080
River Rch & RM=DRYFK,Main            ,17709
     834     447     591     708    1160    1230
River Rch & RM=DRYFK,Main            ,16321
     927     499     658     788    1280    1370
River Rch & RM=DRYFK,Main            ,13806
    1030     554     729     873    1420    1520
River Rch & RM=DRYFK,Main            ,12889
    1150     626     822     982    1590    1710
River Rch & RM=DRYFK,Main            ,10383
    1690     934    1220    1450    2320    2510
River Rch & RM=DRYFK,Main            ,6944
    1880    1040    1350    1600    2560    2770
Boundary for River Rch & Prof#=DRYFK,Main            , 1
Up Type= 0
Dn Type= 3
Dn Slope=0.02852
Boundary for River Rch & Prof#=DRYFK,Main            , 2
Up Type= 0
Dn Type= 3
Dn Slope=0.02852
Boundary for River Rch & Prof#=DRYFK,Main            , 3
Up Type= 0
Dn Type= 3
Dn Slope=0.02852
Boundary for River Rch & Prof#=DRYFK,Main            , 4
Up Type= 0
Dn Type= 3
Dn Slope=0.02852
Boundary for River Rch & Prof#=DRYFK,Main            , 5
Up Type= 0
Dn Type= 3
Dn Slope=0.02852
Boundary for River Rch & Prof#=DRYFK,Main            , 6
Up Type= 0
Dn Type= 3
Dn Slope=0.02852
DSS Import GetInterval= 0
DSS Import GetPeak= 0
DSS Import FillOption= 0

--- DRYFK.g01 (geometry) ---

Geom Title=Geometry
Program Version=6.10

River Reach=DRYFK           ,Main
Reach XY= 30
 2241169.0461158528860.1641263962240761.81694339 529154.21898447
 2240106.8828858529290.2229775642239414.23991413529135.956881896
2238466.71687481529482.0641293082237778.09292397529179.307845056
2237355.19908471  529179.51388142237124.17592472529395.626966223
 2236291.2448478529226.7988918132235807.10605231529686.180847064
2234515.35601114529984.3469173912233578.06293821529966.502136812
2232992.18090789530380.7129225582232482.85384256530309.117921397
 2232123.2630263530670.0791417212230389.89691971530978.767690255
2229856.45489588 531335.18706347 2229896.4249603531758.063842401
2229627.70797805532041.7988392262229136.45403931532153.713969722
2228929.41803606532656.947871387 2227109.5961932 533027.55394528
2226217.33520564 534017.211226972225376.68399981534115.297973067
2224963.93810613534549.9139017312224868.99702306535534.560882553
2223748.37295197536292.6791169792223185.52991755536418.563051566
2221949.55158299537666.4885771882221491.23934288537778.860855892

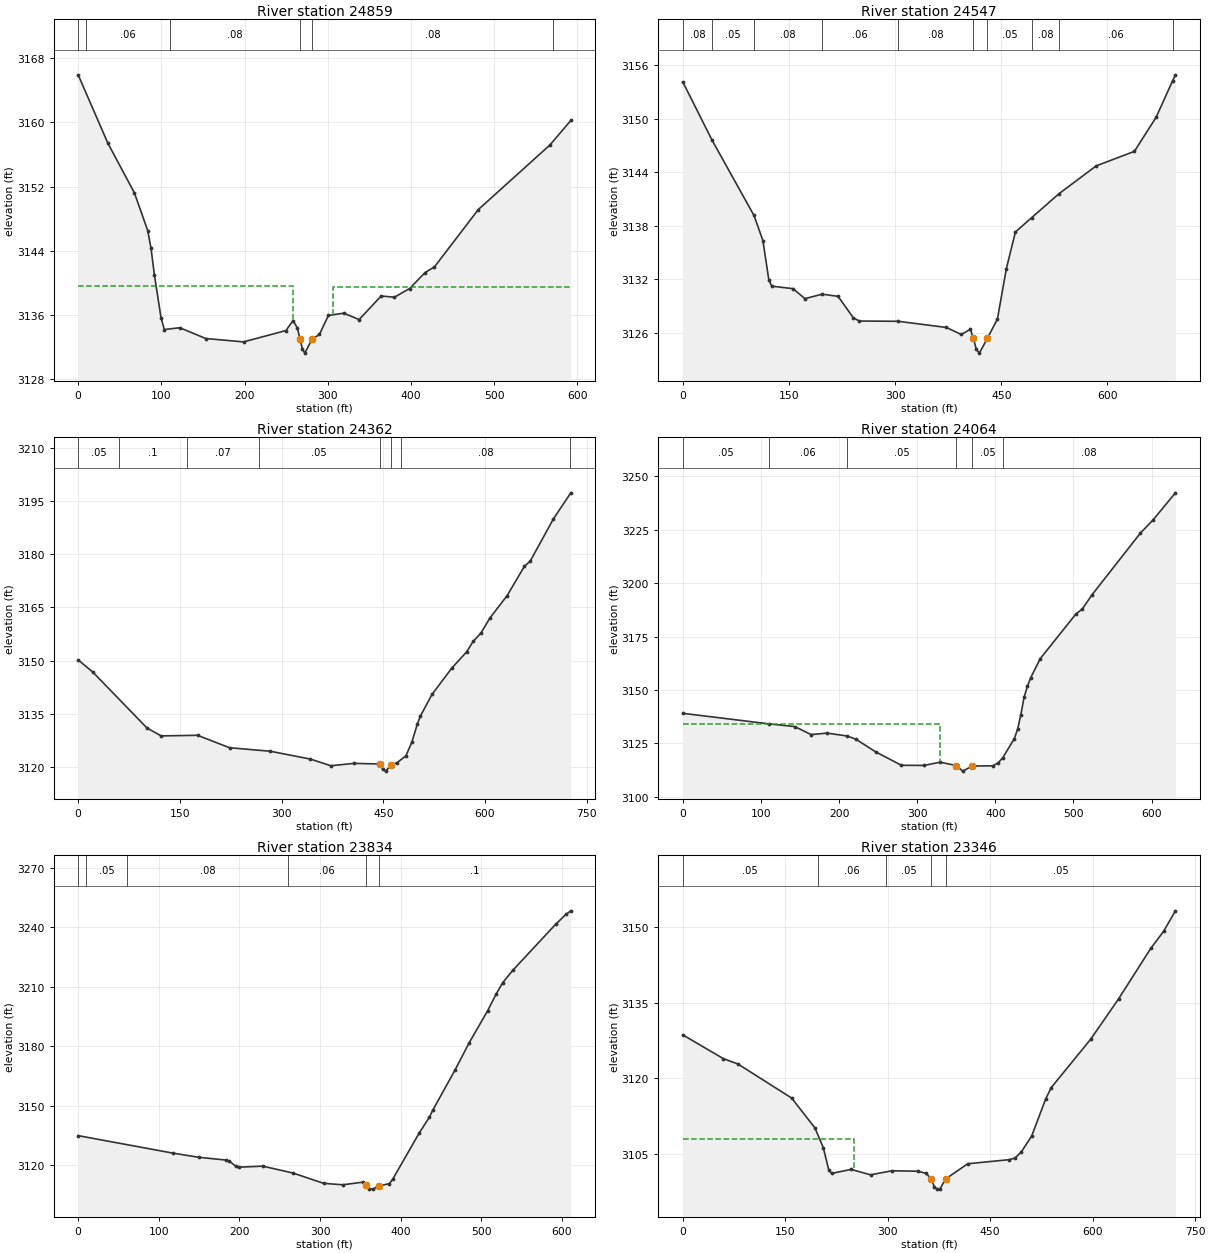
Type RM Length L Ch R = 1 ,24859   ,299.9,311.7,319.4
XS GIS Cut Line= 3
2241041.35633578528649.5371666132241040.92470061528760.313356847
2241404.14268241 529076.42934376
#Sta/Elev= 30
       0  3165.9    35.6 3157.41    67.6 3151.21    83.6 3146.52    87.6 3144.29
    91.6 3141.04    99.6 3135.66   103.6  3134.2   122.2 3134.42   153.4 3133.08
   198.8 3132.66   249.8 3134.07   258.3 3135.31   263.6 3134.38   266.8 3132.96
   269.6 3131.76   272.5 3131.26     281 3132.96   290.1 3133.59   300.8 3135.95
   319.3 3136.23   337.8 3135.44   364.3 3138.37   380.2 3138.22   398.5  3139.3
   417.1 3141.29   428.4    3142     481 3149.12   567.3 3157.18   592.3 3160.22
#Mann= 6 ,-1,0
       0     .08       0      10     .06       0     110     .08       0
   266.8    .045       0     281     .08       0  570.78     .03       0
#XS Ineff= 2 , 0
          258.43 3139.58   306.1         3139.49
Permanent Ineff=
       F       F
Bank Sta=266.8,281
XS Rating Curve= 0 ,0
Exp/Cntr=0.3,0.1

Type RM Length L Ch R = 1 ,24547   ,184.6,184.6,184.3
XS GIS Cut Line= 4
2240903.97576175528665.2356944712240869.58057782528774.153776947
2240992.82998693529119.5387490072241160.50650864529254.253219437
#Sta/Elev= 30
       0 3154.14    41.2 3147.63   100.6 3139.16   113.2 3136.35   121.7 3131.87
   125.9 3131.23   155.7 3130.95   172.6 3129.83   196.9 3130.33   219.4 3130.09
   240.7 3127.71   249.1 3127.32   304.3 3127.29   372.3  3126.6   393.5 3125.81
   406.2 3126.39   410.5 3125.42   414.7 3124.14     419 3123.72   430.43125.391
   444.5 3127.53   457.2 3133.21   469.9  3137.3     493 3138.92   531.4 3141.59
   584.1 3144.72   638.1 3146.35   668.8 3150.18   692.2 3154.29     696 3154.93
#Mann= 10 ,-1,0
       0     .08       0    41.2     .05       0   100.6     .08       0
   196.9     .06       0   304.3     .08       0   410.5    .045       0
   430.4     .05       0     493     .08       0   531.4     .06       0
   692.2      .1       0
Bank Sta=410.5,430.4
XS Rating Curve= 0 ,0
Exp/Cntr(USF)=0,0
Exp/Cntr=0.3,0.1

Type RM Length L Ch R = 1 ,24362   ,296.1,298.8,299.8
XS GIS Cut Line= 3
2240753.90259537528703.2546326932240706.70824346528872.837365956
2240897.04185311529389.362466174
#Sta/Elev= 30
       0 3150.17    21.4 3146.77   101.6 3130.94   122.4 3128.73     176  3128.9
   223.3 3125.39   283.3  3124.4   342.5 3122.19   372.5 3120.31   406.6 3120.98
     445  3120.8   449.2 3119.29   453.5 3118.79     462 3120.59   470.3 3121.18
   483.3  3123.1   492.1 3126.97   500.4 3132.22   504.6 3134.29   521.7 3140.41
   551.2 3147.91   572.8 3152.42   582.4 3155.37   594.2 3157.82   606.9 3161.91
   632.5 3168.29   658.1 3176.59   666.6 3178.04   700.8 3189.95   726.5 3197.31
#Mann= 8 ,-1,0
       0     .05       0      60      .1       0     160     .07       0
  266.03     .05       0     445    .045       0     462     .05       0
  476.03     .08       0  726.03      .1       0
Bank Sta=445,462
XS Rating Curve= 0 ,0
Exp/Cntr=0.3,0.1

Type RM Length L Ch R = 1 ,24064   ,229.5,229.5,229.5
XS GIS Cut Line= 3
2240541.39319772528850.1098081472240482.63475849 529080.88959738
2240581.52091232529460.624323075
#Sta/Elev= 30
       0 3139.12   110.5 3134.16   143.5 3132.89   164.1 3129.16   184.8 3129.84
   210.8 3128.47   221.9 3126.92   246.7 3121.11   279.8 3114.78   308.7 3114.72
   329.4 3116.24     350 3114.67   358.3 3112.05   370.5 3114.44   397.1 3114.54
   403.8 3115.95   409.6 3118.36   424.4 3127.29   428.6 3131.75   432.7 3138.54
   436.8 3146.59     441 3151.68   445.1 3155.61   457.5  3164.7     503 3185.52
   511.2 3187.87   523.6 3194.49   585.6 3223.42   602.2 3229.75   630.5  3242.3
#Mann= 6 ,-1,0
       0     .05       0   110.5     .06       0   210.8     .05       0
     350    .045       0   370.5     .05       0   409.6     .08       0
#XS Ineff= 2 , 0
       0   329.4 3134.17               0
Permanent Ineff=
       F       F
Bank Sta=350,370.5
XS Rating Curve= 0 ,0
Exp/Cntr(USF)=0,0
Exp/Cntr=0.3,0.1

Type RM Length L Ch R = 1 ,23834   ,479.9,488.1,496.2
XS GIS Cut Line= 3
2240305.31205706528899.7891317752240251.51018594529103.405474013
2240352.42949379529491.018468972
#Sta/Elev= 30
       0 3134.84   117.3 3126.04   149.3 3123.93   183.5 3122.52   187.6 3121.99
   195.9  3119.3     200 3118.94     229 3119.44   266.2 3116.01   304.4 3110.77
   328.2 3110.04     353 3111.36   357.1  3109.9   361.2 3108.13   365.4 3107.85
   373.3 3109.47     386 3110.63   390.2 3112.89   423.2 3136.29   435.7 3144.17
   439.8 3147.65   467.3 3167.82   485.2 3181.85   507.8  3197.8   518.3 3206.15
   526.6 3212.04     539 3218.24   592.7 3241.69   605.1 3246.53   611.1 3248.31
#Mann= 6 ,-1,0
       0     .08       0      10     .05       0      60     .08       0
   260.6     .06       0   357.1    .045       0   373.3      .1       0
Bank Sta=357.1,373.3
XS Rating Curve= 0 ,0
Exp/Cntr=0.3,0.1

Type RM Length L Ch R = 1 ,23346   ,241.2,241.4,242.7
XS GIS Cut Line= 4
 2239973.2484282528914.6620401562239854.08084804529017.871264658
 2239788.4452859529374.9054482742239834.27026495529570.139776082
#Sta/Elev= 30
       0 3128.59    59.3 3123.88    80.8  3122.8   159.4 3116.04   193.5  3110.1
   205.7  3106.2   213.9 3101.67     218 3101.07   246.4 3101.87   274.9 3100.79
   306.4  3101.6   344.2  3101.5   356.2 3101.08   363.7    3100   368.4 3098.31
   372.5 3097.95   376.6 3097.99   384.7 3099.97   417.2 3102.99   478.3 3103.81
   486.4 3104.14   495.4 3105.31   510.8  3108.5   531.2 3115.84   539.4 3118.12
     597  3127.7     638 3135.74   685.1 3145.77   703.8 3149.14   721.2 3153.23
#Mann= 5 ,-1,0
       0     .05       0  197.65     .06       0  297.65     .05       0
   363.7    .045       0   384.7     .05       0
#XS Ineff= 2 , 0
          250.16 3107.81
Permanent Ineff=
       F       F
Bank Sta=363.7,384.7
XS Rating Curve= 0 ,0
Exp/Cntr=0.3,0.1

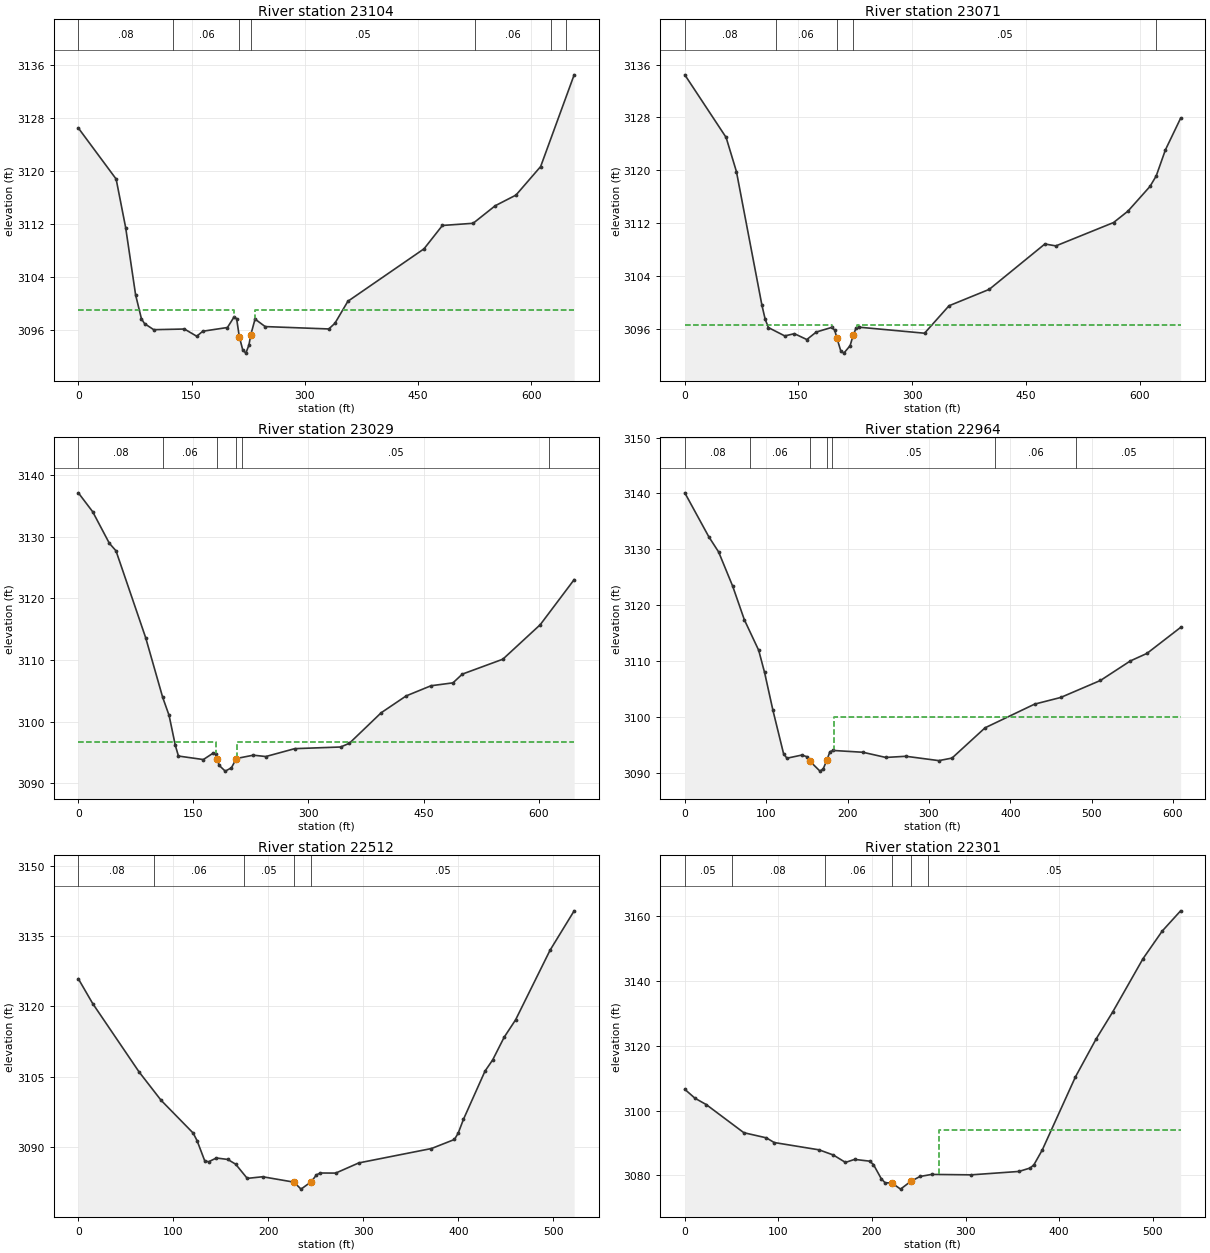
Type RM Length L Ch R = 1 ,23104   ,33.5,33.9,34.4
XS GIS Cut Line= 3
2239594.44870401528930.4798047512239620.99243446529001.617002357
2239513.75576344529572.838081637
#Sta/Elev= 30
       0 3126.47    50.1 3118.76    62.7 3111.44    75.9 3101.27    83.6 3097.67
    87.7 3096.93    99.9 3096.01   140.6 3096.11   156.9 3095.02     165 3095.78
   197.6 3096.34   206.5 3097.95   209.8 3097.67   213.3 3094.97   217.9 3092.95
     222 3092.47   226.1 3093.69   228.53095.229   234.2 3097.61   247.6 3096.48
   331.9 3096.12     340 3096.97   357.2  3100.3   458.1 3108.22   482.5 3111.75
   523.2 3112.08   552.5 3114.73     580 3116.34   612.7 3120.65   657.1  3134.5
#Mann= 7 ,-1,0
       0     .08       0  125.93     .06       0   213.3    .045       0
   228.5     .05       0  525.93     .06       0  625.93     .03       0
  645.93      .1       0
#XS Ineff= 2 , 0
           206.1    3099  233.77         3098.96
Permanent Ineff=
       F       F
Bank Sta=213.3,228.5
XS Rating Curve= 0 ,0
Exp/Cntr(USF)=0,0
Exp/Cntr=0.5,0.3

Type RM Length L Ch R = 1 ,23071   ,41.3,41.1,40.9
XS GIS Cut Line= 3
2239522.59056558528938.4888019392239574.70016855529070.630701527
2239473.95982979529572.756811944
#Sta/Elev= 30
       0 3134.47    54.5 3124.98    68.1 3119.81   101.8 3099.51   106.1 3097.38
   110.4 3096.14   131.9 3094.88   144.6 3095.22     161 3094.33   173.5 3095.47
   193.6 3096.16   197.7 3095.79   200.53094.627   205.8 3092.61   209.9 3092.27
   218.1  3093.4   222.2 3094.99   226.2 3096.13   230.3  3096.2   316.3 3095.29
   348.6 3099.45   401.7 3101.94   475.1 3108.82   489.6 3108.53   565.7 3112.07
   584.7  3113.8   613.8 3117.55     622 3119.14   634.2 3123.11   654.2 3127.89
#Mann= 5 ,-1,0
       0     .08       0     120     .06       0   200.5    .045       0
   222.2     .05       0  622.05      .1       0
#XS Ineff= 2 ,-1
       0  194.08  3096.6  227.66654.1774  3096.6
Permanent Ineff=
       F       F
Bank Sta=200.5,222.2
XS Rating Curve= 0 ,0
Exp/Cntr(USF)=0,0
Exp/Cntr=0.5,0.3

Type RM Length L Ch R = 1 ,23029   ,66.3,65.7,65.4
XS GIS Cut Line= 3
2239490.20066042528952.0018546412239534.56604811529056.297087084
2239438.56818919529580.621620966
#Sta/Elev= 30
       0 3137.15    18.7 3134.08    40.4 3128.96    49.1 3127.73    87.8 3113.61
     110 3103.91   118.3    3101   126.4 3096.15   130.5 3094.39     163 3093.82
   175.2 3094.82   179.3 3094.71   181.2 3093.88   183.4  3092.9   191.5 3091.94
   199.6 3092.48     206 3093.99   228.1 3094.53   244.4 3094.31   282.1 3095.59
     342 3095.86   353.3 3096.46   394.8 3101.42   427.4 3104.16   459.8 3105.81
   488.4 3106.28   500.6  3107.7   553.4 3110.12   602.2 3115.73   646.4 3123.05
#Mann= 6 ,-1,0
       0     .08       0     110     .06       0   181.2    .045       0
     206     .06       0  213.34     .05       0  613.34      .1       0
#XS Ineff= 2 ,-1
       0  179.44  3096.6  207.17646.3794  3096.6
Permanent Ineff=
       F       F
Bank Sta=181.2,206
XS Rating Curve= 0 ,0
Exp/Cntr(USF)=0,0
Exp/Cntr=0.5,0.3

Type RM Length L Ch R = 1 ,22964   ,457.9,452.3,446.1
XS GIS Cut Line= 3
2239412.07231701528978.3503326512239461.68566789529088.954548485
2239379.28633211529570.020557869
#Sta/Elev= 30
       0 3140.12    29.4 3132.28    41.6 3129.52    58.9 3123.38    73.2 3117.38
    90.8 3111.92      98 3107.97   108.3 3101.17   121.4 3093.39   125.5 3092.59
   143.5 3093.15   149.9 3092.88   153.9 3092.04   166.1 3090.28   170.1 3090.68
   174.7  3092.3   178.3 3093.75   182.3 3093.98   218.8 3093.66     247 3092.73
   271.7 3092.94   312.2 3092.16   328.4 3092.62     369 3098.04   429.9 3102.28
   461.9 3103.47   510.8 3106.52   547.6 3110.02   567.9 3111.36   609.3 3116.02
#Mann= 7 ,-1,0
       0     .08       0      80     .06       0   153.9    .045       0
   174.7     .06       0  181.22     .05       0  381.22     .06       0
  481.22     .05       0
#XS Ineff= 2 , 0
                          183.11         3099.96
Permanent Ineff=
       F       F
Bank Sta=153.9,174.7
XS Rating Curve= 0 ,0
Exp/Cntr=0.3,0.1

Type RM Length L Ch R = 1 ,22512   ,213.2,210.7,208.2
XS GIS Cut Line= 4
2239096.12140627529074.3132134412239067.91305604529225.802501705
2239090.89763771529372.068021409 2239115.9717268529590.421547251
#Sta/Elev= 30
       0  3125.9    15.1 3120.62    63.9 3106.04    87.1 3099.98   120.9 3092.98
     125 3091.36   133.1 3087.04   137.2 3086.87   145.3 3087.67   157.3 3087.36
   165.6 3086.35   177.8 3083.32     194 3083.67     2273082.518   234.4 3081.03
   245.33082.628   250.6 3084.07   254.7 3084.47   270.9 3084.45   295.2 3086.62
   371.7 3089.69   395.9 3091.62   399.9    3093   405.4 3095.93   428.1 3106.22
   436.1 3108.58   448.2 3113.42   460.3 3117.16   496.5 3131.98   521.9 3140.39
#Mann= 5 ,-1,0
       0     .08       0      80     .06       0  174.09     .05       0
     227    .045       0   245.3     .05       0
Bank Sta=227,245.3
XS Rating Curve= 0 ,0
Exp/Cntr(USF)=0,0
Exp/Cntr=0.3,0.1

Type RM Length L Ch R = 1 ,22301   ,191.9,191,190.1
XS GIS Cut Line= 5
2238861.05182104529098.3425488212238848.51477649529237.294792539
2238882.99164899529363.7099917112238925.82655119529427.439968153
2238942.54261058 529609.22711407
#Sta/Elev= 30
       0  3106.6    10.9 3103.84    22.9 3101.89    63.1  3093.2    87.2 3091.61
    95.5 3090.17   143.5 3087.91   158.7 3086.32   171.7 3084.03   181.5 3084.96
   197.4 3084.42   201.6 3083.38   209.9 3079.04     214 3077.75   221.33077.677
   230.6 3075.78   241.4 3078.16   251.3 3079.68   263.8 3080.32   306.1 3080.19
   357.1 3081.24   369.2 3082.31   373.2 3083.34   382.1 3087.91   417.4 3110.38
   439.4 3122.05   457.3 3130.47   489.7 3146.93   510.3 3155.48   529.9  3161.7
#Mann= 6 ,-1,0
       0     .05       0      50     .08       0  149.52     .06       0
   221.3    .045       0   241.4     .06       0  259.52     .05       0
#XS Ineff= 2 , 0
                           271.5         3094.17
Permanent Ineff=
       F       F
Bank Sta=221.3,241.4
XS Rating Curve= 0 ,0
Exp/Cntr(USF)=0,0
Exp/Cntr=0.3,0.1

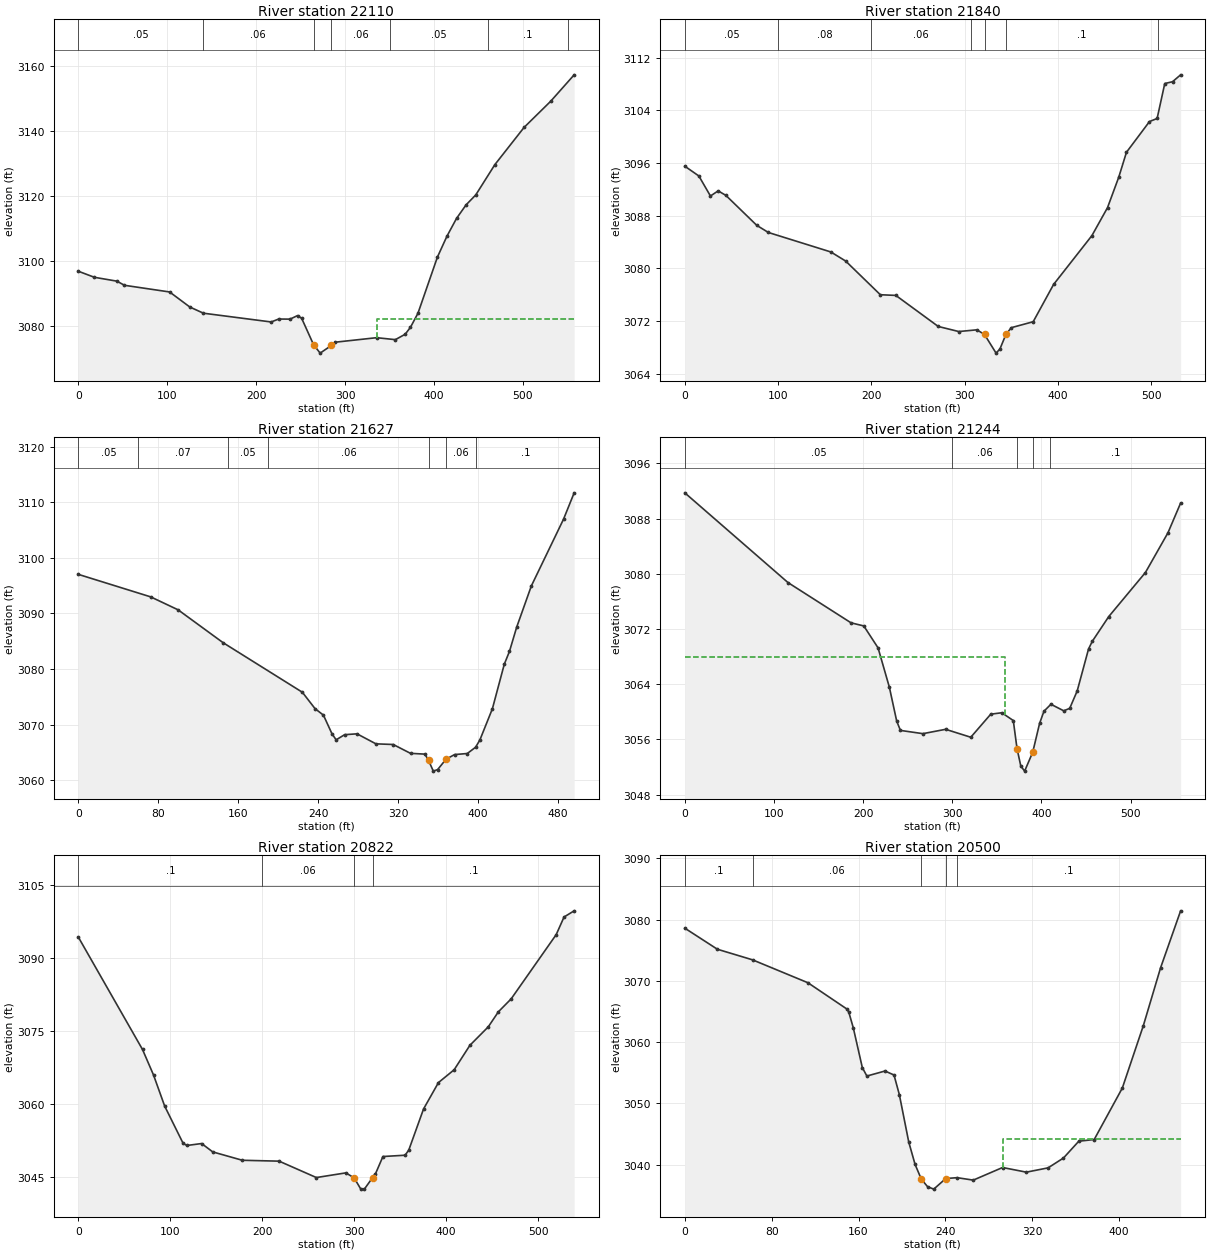
Type RM Length L Ch R = 1 ,22110   ,267.9,269.8,271.1
XS GIS Cut Line= 3
2238601.61333771529120.1742730082238732.69348808529498.850262964
2238837.88126307529615.365952181
#Sta/Elev= 30
       0 3096.92      18 3095.06    43.4 3093.87    51.9  3092.6   102.7 3090.55
   125.4 3085.93   140.7 3084.03   216.9 3081.34   225.4 3082.24   238.1 3082.21
   246.6  3083.3   251.2 3082.46   264.6 3074.35     272 3071.77   284.7 3074.14
   289.1 3075.13   335.5 3076.51   356.6 3075.91   367.6 3077.56   373.6 3079.71
     382 3084.01   403.9 3101.26   414.6 3107.67   425.4 3113.14   436.2 3117.32
     447 3120.34   468.5 3129.65   501.4 3141.09   531.3 3149.11   557.7 3157.23
#Mann= 7 ,-1,0
       0     .05       0     140     .06       0   264.6    .045       0
   284.7     .06       0     350     .05       0  460.72      .1       0
  550.72     .05       0
#XS Ineff= 1 ,-1
  335.47557.6938  3082.1
Permanent Ineff=
       F
Bank Sta=264.6,284.7
XS Rating Curve= 0 ,0
Exp/Cntr(USF)=0,0
Exp/Cntr=0.3,0.1

Type RM Length L Ch R = 1 ,21840   ,201.2,213,223.7
XS GIS Cut Line= 3
2238517.32784973529150.5802344292238437.92656761529447.290288684
2238490.16425322529665.643814527
#Sta/Elev= 30
       0 3095.52    15.1 3094.03    27.5 3090.99    35.8 3091.77    44.1 3091.08
    77.2 3086.53    89.6 3085.45   156.6 3082.49   172.5 3081.11   209.7 3075.99
   226.3 3075.89   271.8 3071.17   293.8  3070.4   313.2 3070.66   321.4 3069.95
   333.8 3067.12   337.9 3067.74   344.5 3070.01   350.2 3070.99   373.6 3071.89
   395.5 3077.56   436.6 3084.98   453.3 3089.22   465.4 3093.87   473.6 3097.63
   498.3  3102.3   506.5 3102.77   514.7 3108.08     523 3108.35   531.7  3109.4
#Mann= 7 ,-1,0
       0     .05       0     100     .08       0     200     .06       0
  307.15      .1       0   321.4    .045       0   344.5      .1       0
  507.15     .05       0
Bank Sta=321.4,344.5
XS Rating Curve= 0 ,0
Exp/Cntr(USF)=0,0
Exp/Cntr=0.3,0.1

Type RM Length L Ch R = 1 ,21627   ,382.9,382.9,382.8
XS GIS Cut Line= 3
2238435.24725596529105.9647351872238302.02337874529252.652485782
2238205.53863748529534.417249623
#Sta/Elev= 30
       0 3097.02    72.4 3092.97    99.8 3090.64   144.8 3084.73   224.1 3075.81
   236.8 3072.86   245.2 3071.69   253.7 3068.35   257.9 3067.25   266.4 3068.18
   278.8 3068.33   297.7 3066.53     315 3066.41   332.3 3064.82   346.7 3064.68
   350.3 3063.56   355.1 3061.62   359.4 3061.89   367.8 3063.76   376.4  3064.6
   389.1 3064.79   397.4 3065.92   401.7 3067.23   414.2 3072.84   426.1 3080.85
   431.3 3083.17   438.5 3087.52   453.2 3094.95   485.4 3106.96     496 3111.69
#Mann= 7 ,-1,0
       0     .05       0      60     .07       0     150     .05       0
     190     .06       0   350.3    .045       0   367.8     .06       0
  398.16      .1       0
Bank Sta=350.3,367.8
XS Rating Curve= 0 ,0
Exp/Cntr=0.3,0.1

Type RM Length L Ch R = 1 ,21244   ,426.6,422.4,418.6
XS GIS Cut Line= 3
2238112.76722056528893.6319849632237996.60761654529043.796298257
2237880.06935087529391.149791994
#Sta/Elev= 30
       0 3091.74   115.7 3078.74   186.5  3072.9   200.8 3072.45   216.8 3069.27
   229.5 3063.56   237.7 3058.66   241.9 3057.31   267.1 3056.84   292.6 3057.47
   320.8 3056.32   343.2 3059.66   355.6 3059.87   368.5 3058.74   372.7 3054.66
   376.9 3052.16   381.2 3051.41   390.3 3054.15     398 3058.33   402.9 3060.09
   410.7  3061.1   425.1 3060.15   431.8 3060.51   440.2 3063.04   452.9 3069.11
   457.1 3070.22   475.6 3073.81   516.7 3080.19     542 3085.95   556.2 3090.26
#Mann= 5 ,-1,0
       0     .05       0  299.85     .06       0   372.7    .045       0
   390.3     .06       0  409.85      .1       0
#XS Ineff= 2 , 0
          358.88 3067.89
Permanent Ineff=
       F       F
Bank Sta=372.7,390.3
XS Rating Curve= 0 ,0
Exp/Cntr=0.3,0.1

Type RM Length L Ch R = 1 ,20822   ,339.7,322,310.4
XS GIS Cut Line= 3
2237555.18516347528855.8006972922237513.70517483529242.891702753
2237565.98361654529383.501066568
#Sta/Elev= 30
       0 3094.21    69.8 3071.11    81.8 3065.86    93.9 3059.48     114 3051.81
   118.1 3051.38   134.1 3051.78   146.2 3050.06   178.4 3048.34   218.4 3048.16
   258.9 3044.79     291 3045.75     300 3044.72   307.1 3042.46   311.1 3042.41
   320.1 3044.79   323.2 3045.56   331.3 3049.11   355.4 3049.38   359.4 3050.43
   375.5 3058.89   391.7 3064.31   408.8 3066.95   425.9 3071.97   445.9 3075.77
   456.9 3078.86   470.8 3081.52   519.8 3094.73   528.3 3098.34   539.3 3099.61
#Mann= 4 ,-1,0
       0      .1       0     200     .06       0     300    .045       0
   320.1      .1       0
Bank Sta=300,320.1
XS Rating Curve= 0 ,0
Exp/Cntr=0.3,0.1

Type RM Length L Ch R = 1 ,20500   ,170.2,168.5,165.7
XS GIS Cut Line= 4
2237139.36247983 529020.411834892237196.06126379529211.664449439
 2237245.9900437529280.2107404942237372.08136922529397.839560947
#Sta/Elev= 30
       0 3078.62      30 3075.18    62.4 3073.45   113.4 3069.71   149.3 3065.42
     151 3064.94   155.2 3062.35   163.5 3055.87   167.7 3054.48   184.4  3055.3
   192.7 3054.65   197.6 3051.46   206.3 3043.69   212.1 3040.06   217.8 3037.67
   223.6 3036.42   229.3 3036.02   240.4 3037.75   250.8 3037.89   265.7 3037.49
   292.7 3039.55   314.6 3038.79   334.6 3039.49   348.8  3041.1   362.9 3043.84
   377.1 3044.12     403 3052.52   422.4 3062.73   438.2 3072.13   456.7 3081.45
#Mann= 5 ,-1,0
       0      .1       0    62.4     .06       0   217.8    .045       0
   240.4     .06       0   250.8      .1       0
#XS Ineff= 2 , 0
       0                   292.7       0 3044.17
Permanent Ineff=
       F       F
Bank Sta=217.8,240.4
XS Rating Curve= 0 ,0
Exp/Cntr(USF)=0,0
Exp/Cntr=0.3,0.1

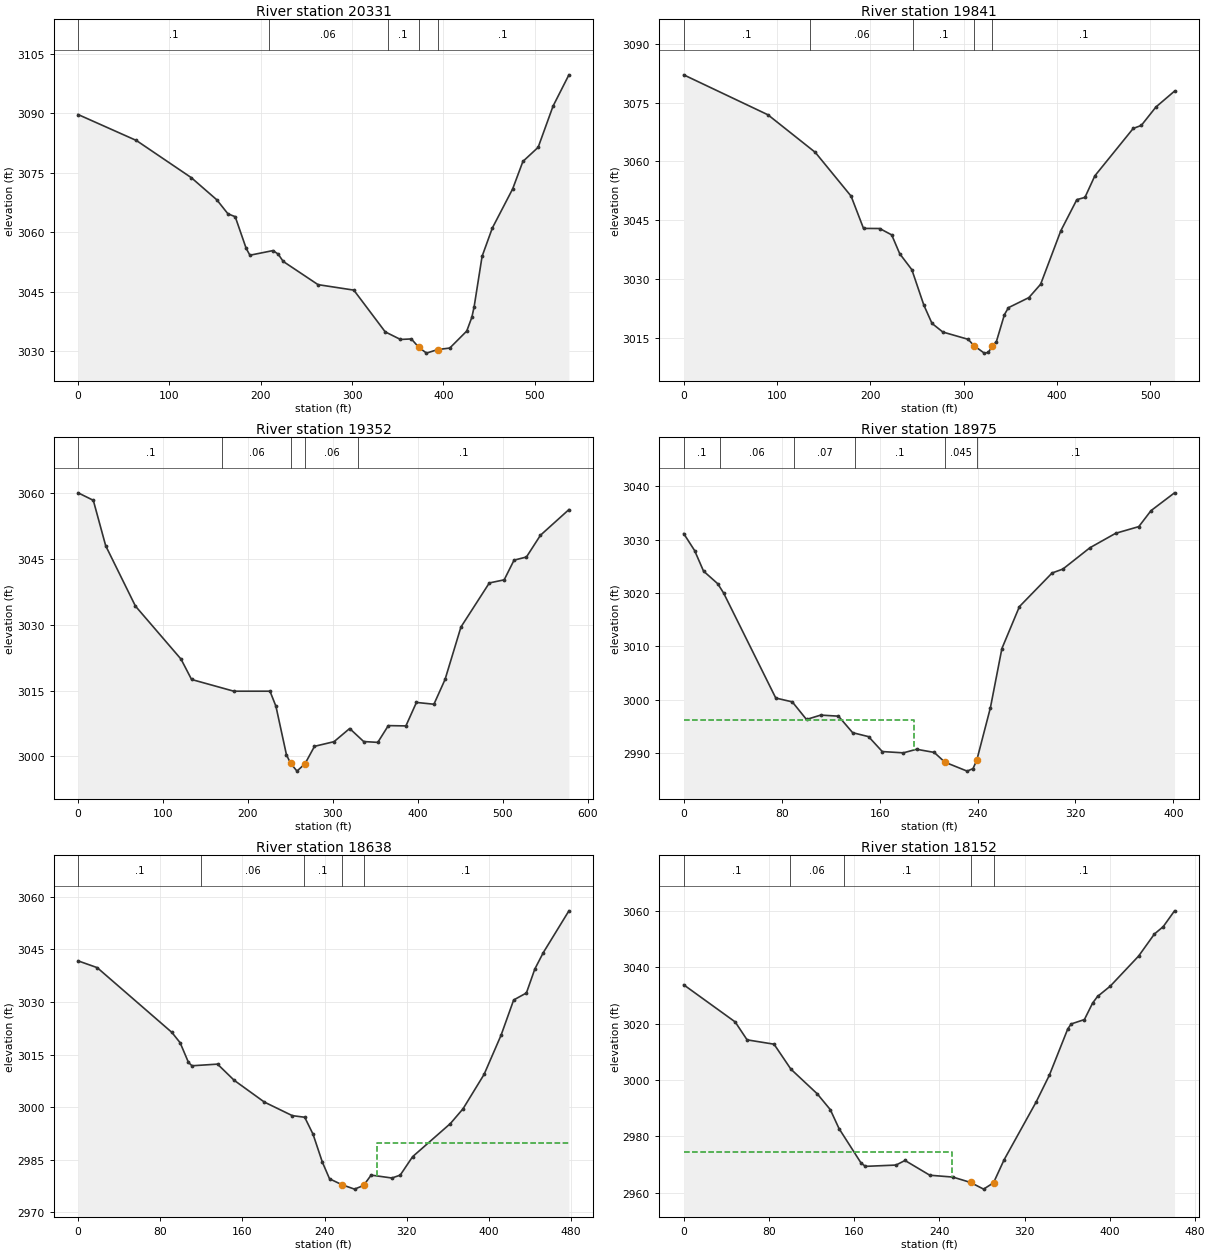
Type RM Length L Ch R = 1 ,20331   ,460.7,490.5,508
XS GIS Cut Line= 3
2237022.83420384529045.6072684392237039.25853841529253.912678646
2237268.60071338529489.288781964
#Sta/Elev= 30
       0 3089.63    63.8 3083.09     124 3073.71     152 3068.11   164.1  3064.6
   172.1 3063.86   184.1 3055.88   188.2 3054.15   213.5 3055.32   219.1 3054.44
   224.7 3052.58   262.8 3046.73     302 3045.35   336.4 3034.82   353.1 3032.91
     365 3033.04   373.1 3030.95   381.6 3029.46   393.7 3030.35   407.1 3030.74
   425.7 3035.03   431.3 3038.51   433.8 3041.17   442.5 3053.87   453.7    3061
     476 3070.88   487.2  3077.8   503.9 3081.36   520.2 3091.74   537.6 3099.64
#Mann= 5 ,-1,0
       0      .1       0  208.95     .06       0  338.95      .1       0
   373.1    .045       0   393.7      .1       0
Bank Sta=373.1,393.7
XS Rating Curve= 0 ,0
Exp/Cntr=0.3,0.1

Type RM Length L Ch R = 1 ,19841   ,502.3,488.5,479.2
XS GIS Cut Line= 3
2236847.54461734529048.888782847 2236759.8440008 529139.19722397
2236610.10952461529510.210933246
#Sta/Elev= 30
       0  3082.1    90.3 3071.89     141  3062.3   179.4 3051.11   192.7 3042.87
     210 3042.85   222.9 3041.22   231.5 3036.41   244.5 3032.33   257.4 3023.25
   266.1 3018.61   277.7 3016.41   304.9 3014.54   310.9 3012.96   322.1 3011.02
   326.4 3011.19   330.8 3012.83   335.1 3013.97   343.7 3020.85     348 3022.63
   369.9  3025.2   382.5 3028.61   404.1 3042.25   421.3 3050.22     430  3050.8
   440.6  3056.3   481.7  3068.4   490.4 3069.18   506.1 3073.89     526 3077.94
#Mann= 5 ,-1,0
       0      .1       0  135.88     .06       0  245.88      .1       0
   310.9    .045       0   330.8      .1       0
Bank Sta=310.9,330.8
XS Rating Curve= 0 ,0
Exp/Cntr=0.3,0.1

Type RM Length L Ch R = 1 ,19352   ,393.7,377.7,366.1
XS GIS Cut Line= 3
2236185.75138346528983.8917493652236293.66047619529396.361964904
 2236372.2926792 529525.77117545
#Sta/Elev= 30
       0 3060.06    17.9 3058.36    32.5    3048    67.5 3034.26   121.2 3022.17
   133.6 3017.54   183.3 3014.87   225.9 3014.87   232.9 3011.44   245.3 3000.38
   250.12998.467   257.7 2996.66   267.2 2998.36   278.3 3002.31   301.3 3003.37
   319.7 3006.37   336.2  3003.4   352.8 3003.21   365.2 3007.03   385.9 3006.96
   398.3 3012.31   418.9  3011.9     432 3017.55   450.7 3029.49   484.1 3039.53
   501.6 3040.24   513.2 3044.72   527.8 3045.44   544.3  3050.4   577.8 3056.24
#Mann= 5 ,-1,0
       0      .1       0     170     .06       0   250.1    .045       0
   267.2     .06       0     330      .1       0
Bank Sta=250.1,267.2
XS Rating Curve= 0 ,0
Exp/Cntr=0.3,0.1

Type RM Length L Ch R = 1 ,18975   ,315.2,336.3,352.7
XS GIS Cut Line= 3
2235856.62623128529394.3181943822236094.45805611529545.086583337
2236203.81822556529592.865298147
#Sta/Elev= 30
       0 3031.12     8.9 3027.95    16.2  3024.1    27.8 3021.74    32.6    3020
    75.2 3000.36    88.7 2999.64   100.3 2996.35   111.9 2997.17   126.4 2996.97
     138 2993.88     151 2993.14   162.2 2990.35   179.4 2990.11   190.2 2990.78
   204.6 2990.19   213.3 2988.37   231.5 2986.69   236.3 2987.16   239.4 2988.75
   250.5 2998.54   259.9 3009.62   274.2 3017.46   300.9 3023.75   309.7 3024.48
   331.8 3028.47   352.8 3031.17   371.7 3032.42   381.7 3035.41   400.9 3038.74
#Mann= 6 ,-1,0
       0      .1       0      30     .06       0      90     .07       0
     140      .1       0   213.3    .045       0   239.4      .1       0
#XS Ineff= 2 , 0
          187.99 2996.23
Permanent Ineff=
       F       F
Bank Sta=213.3,239.4
XS Rating Curve= 0 ,0
Exp/Cntr(USF)=0,0
Exp/Cntr=0.3,0.1

Type RM Length L Ch R = 1 ,18638   ,487.7,486.1,484.4
XS GIS Cut Line= 3
2235732.88591032529426.7885033922235781.69612757529762.172454719
 2235813.7589555 529897.53512218
#Sta/Elev= 30
       0 3041.72    18.6 3039.79    91.3 3021.33    99.4 3018.36   107.5 3012.75
   110.9  3011.8   135.8 3012.27     152 3007.66   181.4 3001.45   208.6 2997.58
   220.7 2997.12   228.8 2992.29   237.9 2984.31   244.9 2979.56   257.1 2977.86
   269.2 2976.62     278 2977.66   285.4 2980.62   305.6 2979.79   313.7 2980.61
   325.8 2985.88   362.6 2995.33   374.9 2999.54   395.4 3009.35   411.9  3020.5
   424.2 3030.57   436.6 3032.56   444.8  3039.4   453.1  3044.1     478 3055.99
#Mann= 5 ,-1,0
       0      .1       0     120     .06       0     220      .1       0
   257.1    .045       0     278      .1       0
#XS Ineff= 2 , 0
                          291.09         2989.78
Permanent Ineff=
       F       F
Bank Sta=257.1,278
XS Rating Curve= 0 ,0
Exp/Cntr=0.3,0.1

Type RM Length L Ch R = 1 ,18152   ,449.7,442.8,439.7
XS GIS Cut Line= 2
2235251.92477932529543.3126120312235358.42013161529991.507643228
#Sta/Elev= 30
       0 3033.77    48.3 3020.61    59.5 3014.25    84.8 3012.71   100.6 3003.87
   125.3 2995.14   137.6 2989.51   145.8  2982.8   166.4 2970.63   170.5  2969.4
   199.3 2969.86   207.7 2971.49     231 2966.26   252.7  2965.6   269.2  2963.7
   281.5 2961.33   290.8 2963.58   300.7 2971.71   330.8 2992.22   343.2 3001.71
   360.5 3018.14   363.7 3019.89   376.1 3021.44   383.8 3027.28   388.4 3029.62
   400.4  3033.3     427 3043.96   441.8 3051.77   450.1 3054.39   460.7 3059.99
#Mann= 5 ,-1,0
       0      .1       0     100     .06       0     150      .1       0
   269.2    .045       0   290.8      .1       0
#XS Ineff= 2 , 0
          251.36 2974.46
Permanent Ineff=
       F       F
Bank Sta=269.2,290.8
XS Rating Curve= 0 ,0
Exp/Cntr=0.3,0.1