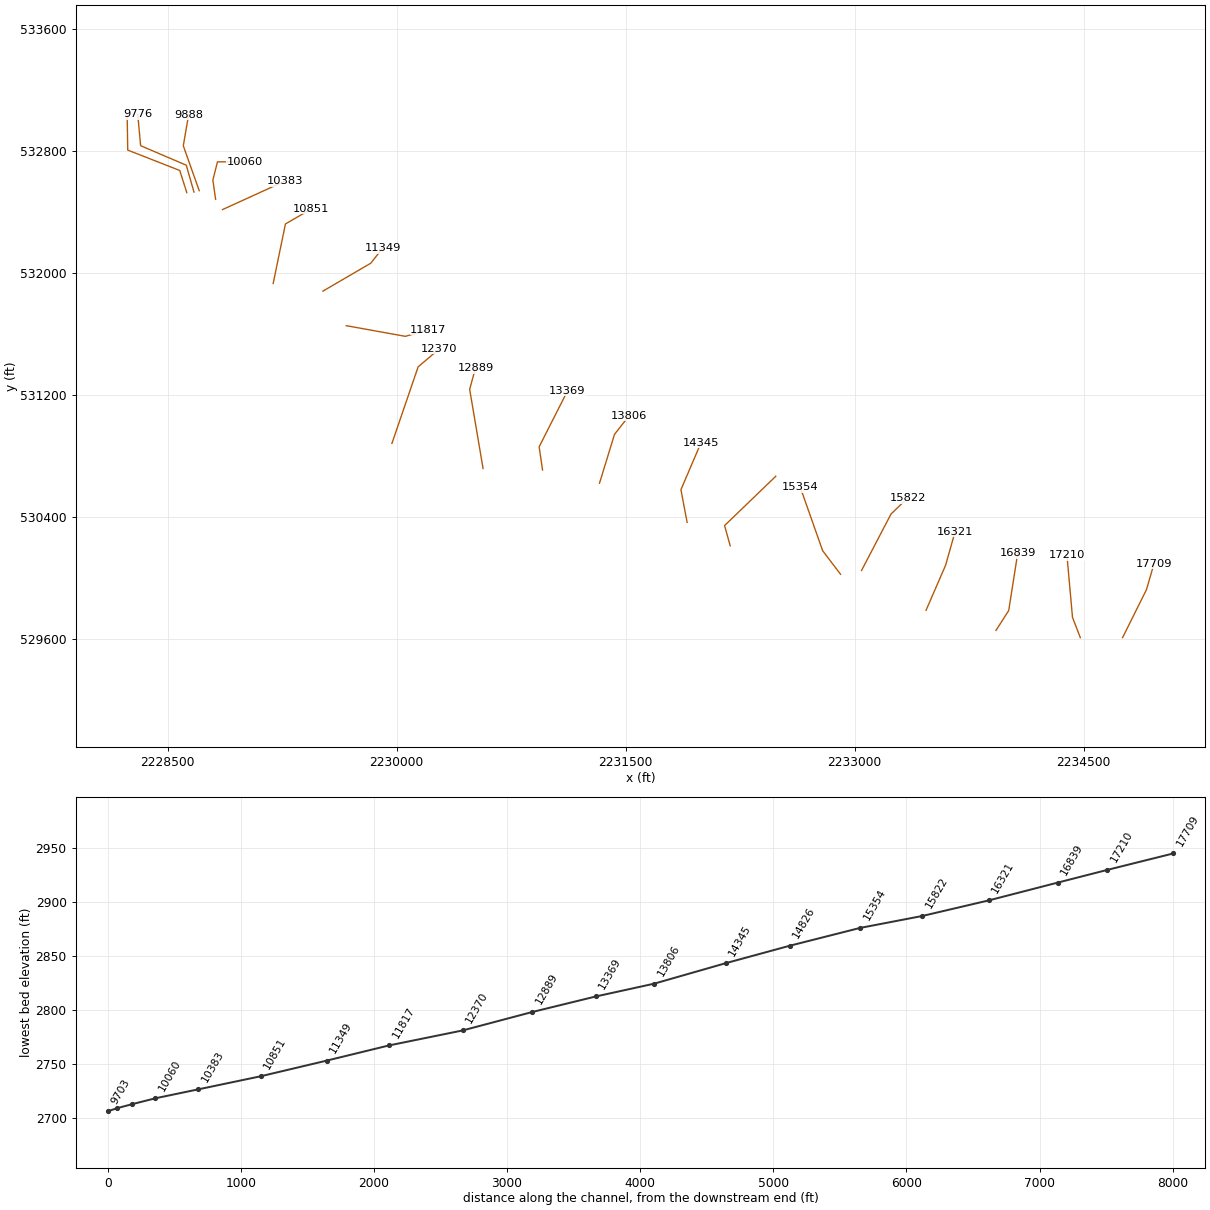
HEC-RAS study DRYFK.prj: DRYFK

--- DRYFK.g01 (geometry) --- (continued)

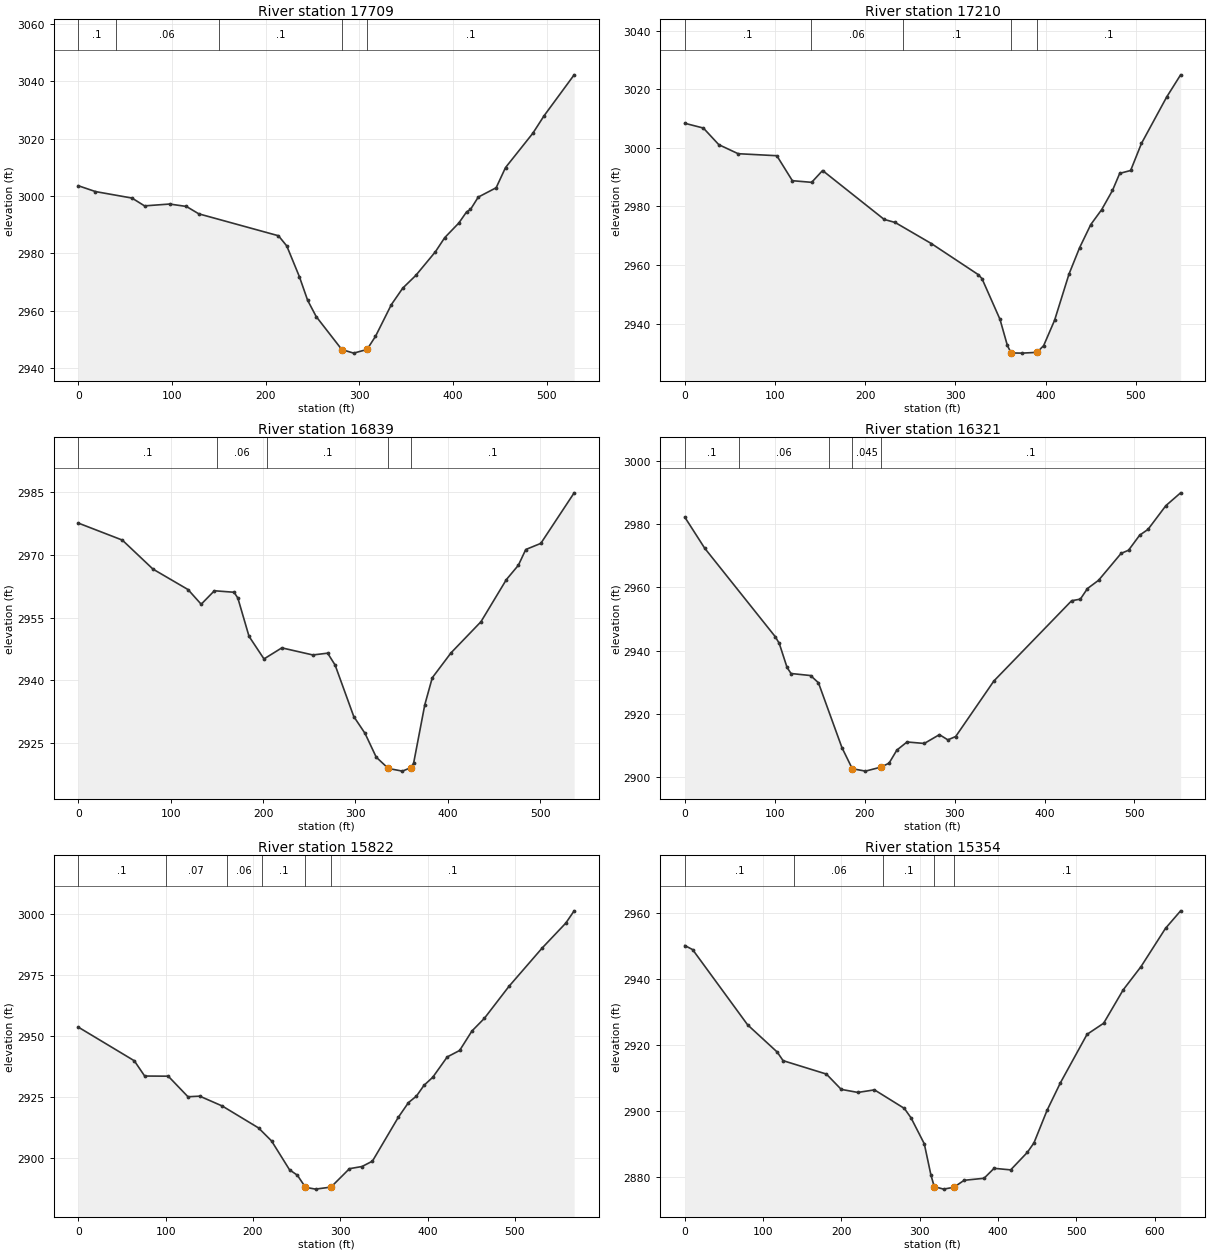
Type RM Length L Ch R = 1 ,17709   ,484.7,499.7,511.3
XS GIS Cut Line= 3
2234754.87373898529609.8805340962234911.37257165529924.517279244
2234961.14202095530095.554368401
#Sta/Elev= 30
       0 3003.58    18.3 3001.55    57.3 2999.29    70.7 2996.57    97.5 2997.21
   115.4 2996.37   128.7 2993.79   213.7 2986.17   222.6 2982.62     236 2971.98
   244.9 2963.68     254 2958.04   281.4 2946.53   294.1  2945.3   308.3 2946.58
   317.3 2951.12   334.3  2962.2   346.5 2967.95   360.4 2972.36   381.3 2980.58
   391.3 2985.52   406.3 2990.59   414.6 2994.47   418.8 2995.33   427.1 2999.63
   446.2 3002.88   456.2 3009.91   485.4 3021.87   497.4 3027.96   529.5  3042.2
#Mann= 5 ,-1,0
       0      .1       0      40     .06       0     150      .1       0
   281.4    .045       0   308.3      .1       0
Bank Sta=281.4,308.3
XS Rating Curve= 0 ,0
Exp/Cntr=0.3,0.1

Type RM Length L Ch R = 1 ,17210   ,375.6,370.4,364.2
XS GIS Cut Line= 3
2234477.98611418529609.9896694092234426.87909266529742.678073548
2234390.55069533530148.361164561
#Sta/Elev= 30
       0 3008.36    20.6 3006.73    37.7 3001.06    59.1 2997.98     102 2997.29
   119.2 2988.77   140.6 2988.21   152.7 2992.24     221 2975.55   233.1 2974.52
   273.2 2967.33   325.4 2956.69   329.4 2955.33   349.3 2941.48   357.5 2932.55
   361.6 2930.01   373.6 2929.94   390.3  2930.2   397.7  2932.5   409.8 2941.14
   425.8 2956.92   437.5 2965.88   449.9 2973.79     462  2978.9     474 2985.46
     482 2991.27   494.1 2992.25   506.1 3001.49     534  3017.3   549.5 3024.89
#Mann= 5 ,-1,0
       0      .1       0     140     .06       0  242.19      .1       0
   361.6    .045       0   390.3      .1       0
Bank Sta=361.6,390.3
XS Rating Curve= 0 ,0
Exp/Cntr=0.3,0.1

Type RM Length L Ch R = 1 ,16839   ,524.7,517.7,510.2
XS GIS Cut Line= 3
2233925.68141855529657.094280138 2234009.0704235529787.482867857
2234068.29923219530164.864239043
#Sta/Elev= 30
       0 2977.67    47.6  2973.6    80.8 2966.65   118.8 2961.74     133 2958.23
   147.3 2961.46   168.6  2961.1   172.7 2959.71   184.8 2950.54     201 2945.13
   220.3 2947.78   253.9 2946.08   269.9 2946.51     278 2943.66   298.2 2931.33
   310.4 2927.29   322.5  2921.6   335.6 2918.89   350.8 2918.25   360.22919.103
     363 2920.15   375.1 2934.16   383.2 2940.62   403.5 2946.59   435.9 2954.04
   463.4 2964.13   476.4 2967.57   484.4 2971.34   500.7 2972.81   536.8 2984.92
#Mann= 5 ,-1,0
       0      .1       0     150     .06       0  204.77      .1       0
   335.6    .045       0   360.2      .1       0
Bank Sta=335.6,360.2
XS Rating Curve= 0 ,0
Exp/Cntr=0.3,0.1

Type RM Length L Ch R = 1 ,16321   ,501.5,499,497.1
XS GIS Cut Line= 3
 2233467.5338797529788.8627052492233595.89216325530084.827468789
2233658.04674887530304.913598505
#Sta/Elev= 30
       0 2982.28    22.1 2972.45   100.6 2944.39     105 2942.29   113.7 2934.65
   118.1 2932.73   139.9 2932.08   148.6 2929.79   174.7 2909.26   186.2 2902.56
   200.9 2901.79     2182903.059   227.1 2904.31   235.8 2908.46   247.1 2911.03
   266.3 2910.56   283.1 2913.35   292.5  2911.7   301.2 2912.76   343.7 2930.37
   430.1 2955.79   439.8  2956.3   447.7 2959.65   460.1 2962.28   485.1 2970.79
   493.4  2971.8   505.8 2976.58     515 2978.39   534.9 2985.93   551.3 2989.99
#Mann= 5 ,-1,0
       0      .1       0      60     .06       0     160      .1       0
   186.2    .045       0     218      .1       0
Bank Sta=186.2,218
XS Rating Curve= 0 ,0
Exp/Cntr=0.3,0.1

Type RM Length L Ch R = 1 ,15822   ,446.7,468.2,485.4
XS GIS Cut Line= 3
2233045.04144871530049.820896985 2233238.0453876530419.889938016
2233346.51404147530524.464184201
#Sta/Elev= 30
       0 2953.67    64.1 2939.91      76 2933.66     103  2933.6   125.6 2925.18
   139.1 2925.42   164.9 2921.39   206.4 2912.43   221.3 2907.12     242 2895.26
   250.9 2893.07   260.22888.118   271.7 2887.37   289.4  2888.2   310.6 2895.74
     325 2896.63   336.9 2898.82   366.5 2916.74   378.2 2922.79   387.3 2925.44
     396 2929.86     406 2933.15   422.6 2941.48   436.8 2944.12   450.9 2952.09
   465.1 2957.26   493.3 2970.36   531.5 2986.12   558.4 2996.25     568 3001.28
#Mann= 6 ,-1,0
       0      .1       0     100     .07       0     170     .06       0
     210      .1       0   260.2    .045       0   289.4      .1       0
Bank Sta=260.2,289.4
XS Rating Curve= 0 ,0
Exp/Cntr=0.3,0.1

Type RM Length L Ch R = 1 ,15354   ,554.5,528.2,504.8
XS GIS Cut Line= 3
2232907.57206015530025.220371421 2232790.4666406530179.365842112
2232644.22351279530593.890759409
#Sta/Elev= 30
       0 2950.18      10 2948.95    80.3  2926.1     118 2917.87   125.5 2915.26
   180.8 2911.19   199.7 2906.55     221 2905.62   242.2  2906.4   280.3 2900.78
   288.8 2897.94   305.8 2890.04   314.3 2880.54   318.5 2877.06   330.4 2876.29
   343.5 2876.85   356.7 2878.97   382.1 2879.58   394.9  2882.6   416.1 2882.13
   437.3 2887.42   445.8  2890.3   462.7 2900.27   479.7 2908.59   513.6 2923.24
   534.8 2926.61   559.8 2936.75   582.5 2943.78   613.8  2955.4   633.1 2960.71
#Mann= 5 ,-1,0
       0      .1       0     140     .06       0  253.58      .1       0
   318.5    .045       0   343.5      .1       0
Bank Sta=318.5,343.5
XS Rating Curve= 0 ,0
Exp/Cntr=0.3,0.1

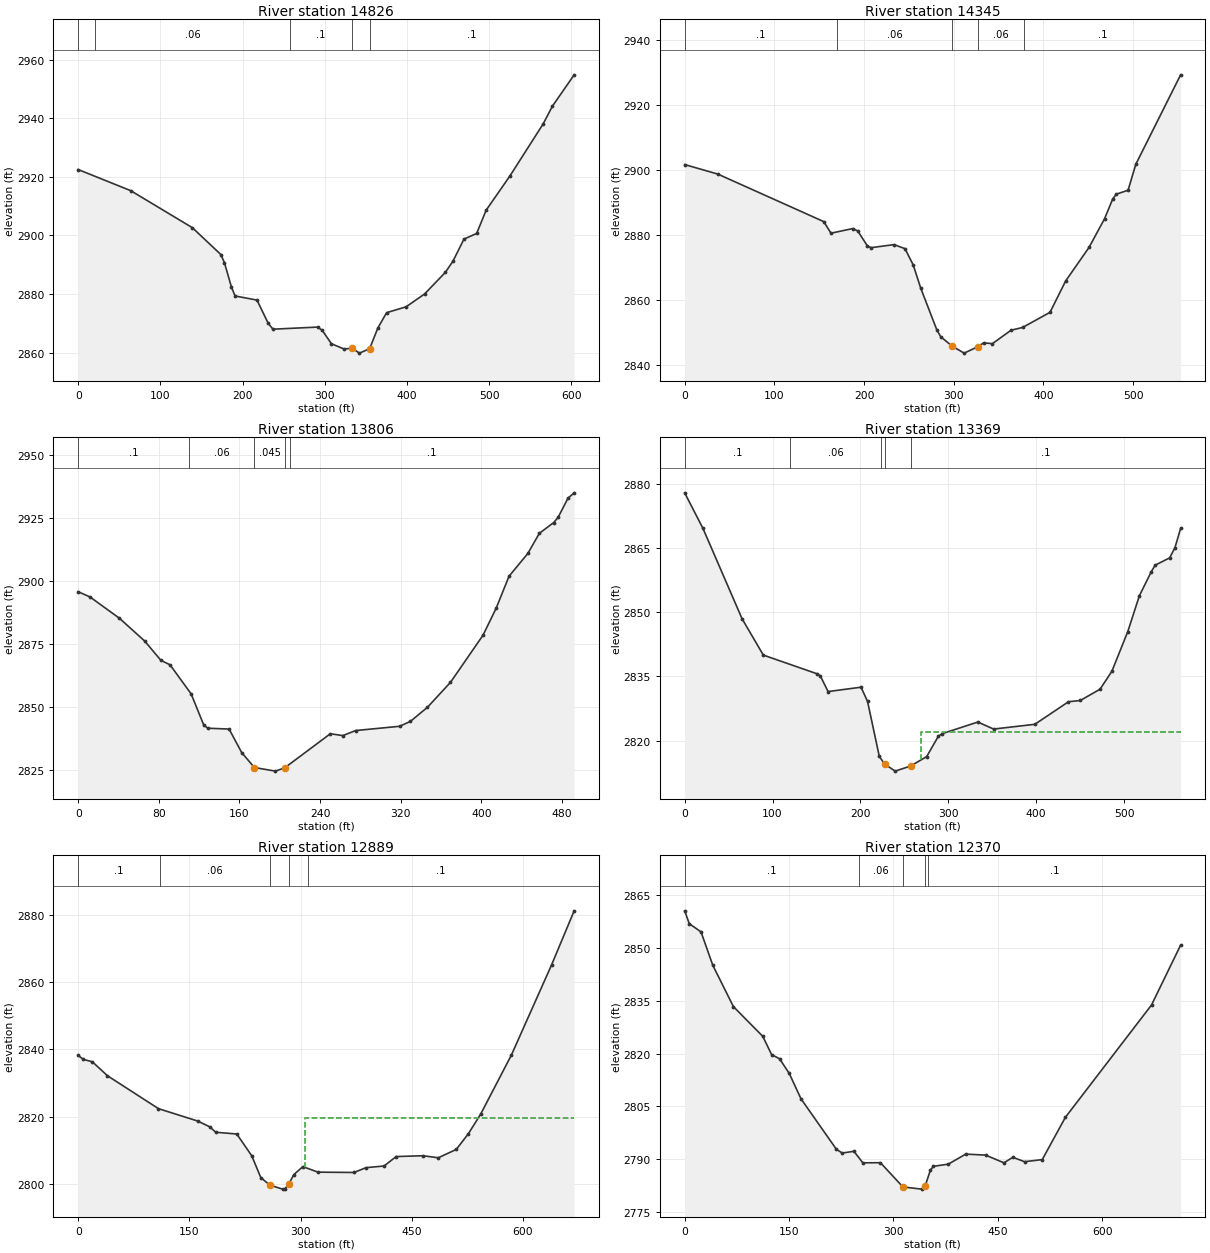
Type RM Length L Ch R = 1 ,14826   ,472.9,480.9,489
XS GIS Cut Line= 3
2232184.79933332530211.6536290692232148.08102006530344.320203013
2232483.30854136530667.453466175
#Sta/Elev= 30
       0 2922.49    63.8 2915.29   138.9 2902.63   173.5 2893.47   177.9 2890.65
   186.4 2882.37   190.8 2879.32   217.5 2877.91   231.1 2869.99   236.9 2867.98
   291.1 2868.69   296.7 2867.63   308.1 2862.99   323.3 2861.22   333.5 2861.46
     342  2859.8   354.5  2861.3   364.6 2868.44   375.2 2873.62   398.9 2875.62
   421.3 2879.99   446.7  2887.4   455.9 2891.23   469.3 2898.75   484.7 2900.66
   496.2  2908.6   525.1 2920.28   565.6 2938.08   576.9 2944.16   603.3 2954.84
#Mann= 5 ,-1,0
       0      .1       0      20     .06       0  257.65      .1       0
   333.5    .045       0   354.5      .1       0
Bank Sta=333.5,354.5
XS Rating Curve= 0 ,0
Exp/Cntr=0.3,0.1

Type RM Length L Ch R = 1 ,14345   ,536.4,539.1,541.7
XS GIS Cut Line= 3
2231902.63643255 530364.888990082231862.15094681530579.574773048
2231993.55092704530887.066319144
#Sta/Elev= 30
       0 2901.75    36.9 2898.82     155 2884.18   163.1  2880.6   187.5 2882.04
   192.9  2881.3   203.8 2876.65   207.9 2876.15   233.4 2877.08   245.6 2875.84
   254.8 2870.82   263.2 2863.64   281.1 2850.82   285.5 2848.69   298.5 2845.74
   311.6 2843.65   326.82845.622   333.3 2846.82   343.1 2846.57   363.8  2850.7
   376.8 2851.57   407.3 2856.22   424.7 2865.87   450.8 2876.23   468.1 2885.06
   477.2 2891.15   481.2 2892.64   494.3 2893.83     503 2901.87   552.9  2929.4
#Mann= 5 ,-1,0
       0      .1       0     170     .06       0   298.5    .045       0
   326.8     .06       0  378.47      .1       0
Bank Sta=298.5,326.8
XS Rating Curve= 0 ,0
Exp/Cntr=0.3,0.1

Type RM Length L Ch R = 1 ,13806   ,440.4,436.8,432.1
XS GIS Cut Line= 3
2231328.78810777530622.097192969 2231427.1692005530942.691719291
     2231524.189531065.695235599
#Sta/Elev= 30
       0 2895.85    11.6 2893.81    40.9 2885.33      66 2876.26      82 2868.63
    91.1 2866.84     112 2855.33   124.6 2842.88   128.7 2841.67   149.7 2841.34
   162.2 2831.99   174.8 2826.07   195.7 2824.64   204.8 2825.94   250.1 2839.47
   262.6 2838.75   275.2 2840.75   318.9 2842.44   329.6  2844.4   346.4 2849.96
   369.3 2859.88   401.6  2878.6   414.7 2889.38   427.4 2902.01   446.1 2911.08
   457.5 2919.06   471.7 2923.31   476.1 2925.39   485.9    2933     492 2935.12
#Mann= 5 ,-1,0
       0      .1       0     110     .06       0   174.8    .045       0
   204.8     .06       0     210      .1       0
Bank Sta=174.8,204.8
XS Rating Curve= 0 ,0
Exp/Cntr=0.3,0.1

Type RM Length L Ch R = 1 ,13369   ,465.8,479.9,496.1
XS GIS Cut Line= 3
2230955.53153383530708.5806276712230933.44871039530860.465600394
2231119.15978808531226.990396554
#Sta/Elev= 30
       0 2877.93    20.8 2869.61    65.3 2848.48    89.5 2839.98   150.2 2835.64
   154.3 2835.13   163.2 2831.45   200.7 2832.47   208.1 2829.15   221.5 2816.28
   227.5 2814.52   239.5 2812.84   257.2 2814.04   275.4 2816.24   288.8 2821.03
   293.3 2821.62   333.6 2824.32   351.6 2822.68   398.5 2823.79   436.8 2829.07
   450.2 2829.36   472.7    2832   486.1 2836.16   504.3 2845.49   517.5 2853.87
     531 2859.48   535.4    2861   551.9 2862.72   557.9 2865.08   564.4 2869.59
#Mann= 5 ,-1,0
       0      .1       0     120     .06       0  223.48      .1       0
   227.5    .045       0   257.2      .1       0
#XS Ineff= 2 , 0
                          269.12          2822.1
Permanent Ineff=
       F       F
Bank Sta=227.5,257.2
XS Rating Curve= 0 ,0
Exp/Cntr=0.3,0.1

Type RM Length L Ch R = 1 ,12889   ,525.3,519.6,503.4
XS GIS Cut Line= 3
2230566.14563575530718.3170478832230478.29071535531237.566200213
2230516.04428519531374.863808651
#Sta/Elev= 30
       0  2838.2       7 2837.02    19.1 2836.31    39.4 2832.17   108.3 2822.35
   161.1 2818.67   177.3 2816.96   185.5 2815.33   213.9  2814.8   234.1 2808.31
   246.3 2801.83   258.5 2799.57   275.6 2798.38   278.8 2798.43   284.3 2799.98
   290.9 2802.72   303.1 2805.08   323.4 2803.44     372 2803.34   388.3 2804.78
   412.6 2805.27   428.9 2808.08     465 2808.33   485.7 2807.72     510 2810.21
   526.2 2814.85   542.8 2820.69   584.3  2838.3   638.5 2865.16     669 2881.29
#Mann= 5 ,-1,0
       0      .1       0     110     .06       0   258.5    .045       0
   284.3     .06       0     310      .1       0
#XS Ineff= 2 , 0
                          306.46         2819.62
Permanent Ineff=
       F       F
Bank Sta=258.5,284.3
XS Rating Curve= 0 ,0
Exp/Cntr=0.3,0.1

Type RM Length L Ch R = 1 ,12370   ,594.4,553.3,516.2
XS GIS Cut Line= 3
2229969.21511807 530882.949321912230140.84593845531384.646994977
2230280.00457617531502.782530773
#Sta/Elev= 30
       0 2860.62     6.6 2856.96    23.5 2854.62    40.4 2845.13      70 2833.37
   112.3 2824.88     125 2819.68   136.4 2818.51   150.3 2814.34   167.2 2807.11
     218 2792.77   226.4 2791.68   243.3 2792.18     256  2788.9   281.4 2788.93
   313.7 2782.03   340.6 2781.41   345.8 2782.41   353.2 2786.83   357.5  2787.9
   378.9 2788.52     404 2791.38   432.5 2791.09   458.9  2788.9   471.6 2790.47
   488.5 2789.22   513.9 2789.81   547.2 2801.85     671 2833.83   712.8 2850.86
#Mann= 5 ,-1,0
       0      .1       0     250     .06       0   313.7    .045       0
   345.8     .06       0     350      .1       0
Bank Sta=313.7,345.8
XS Rating Curve= 0 ,0
Exp/Cntr=0.3,0.1

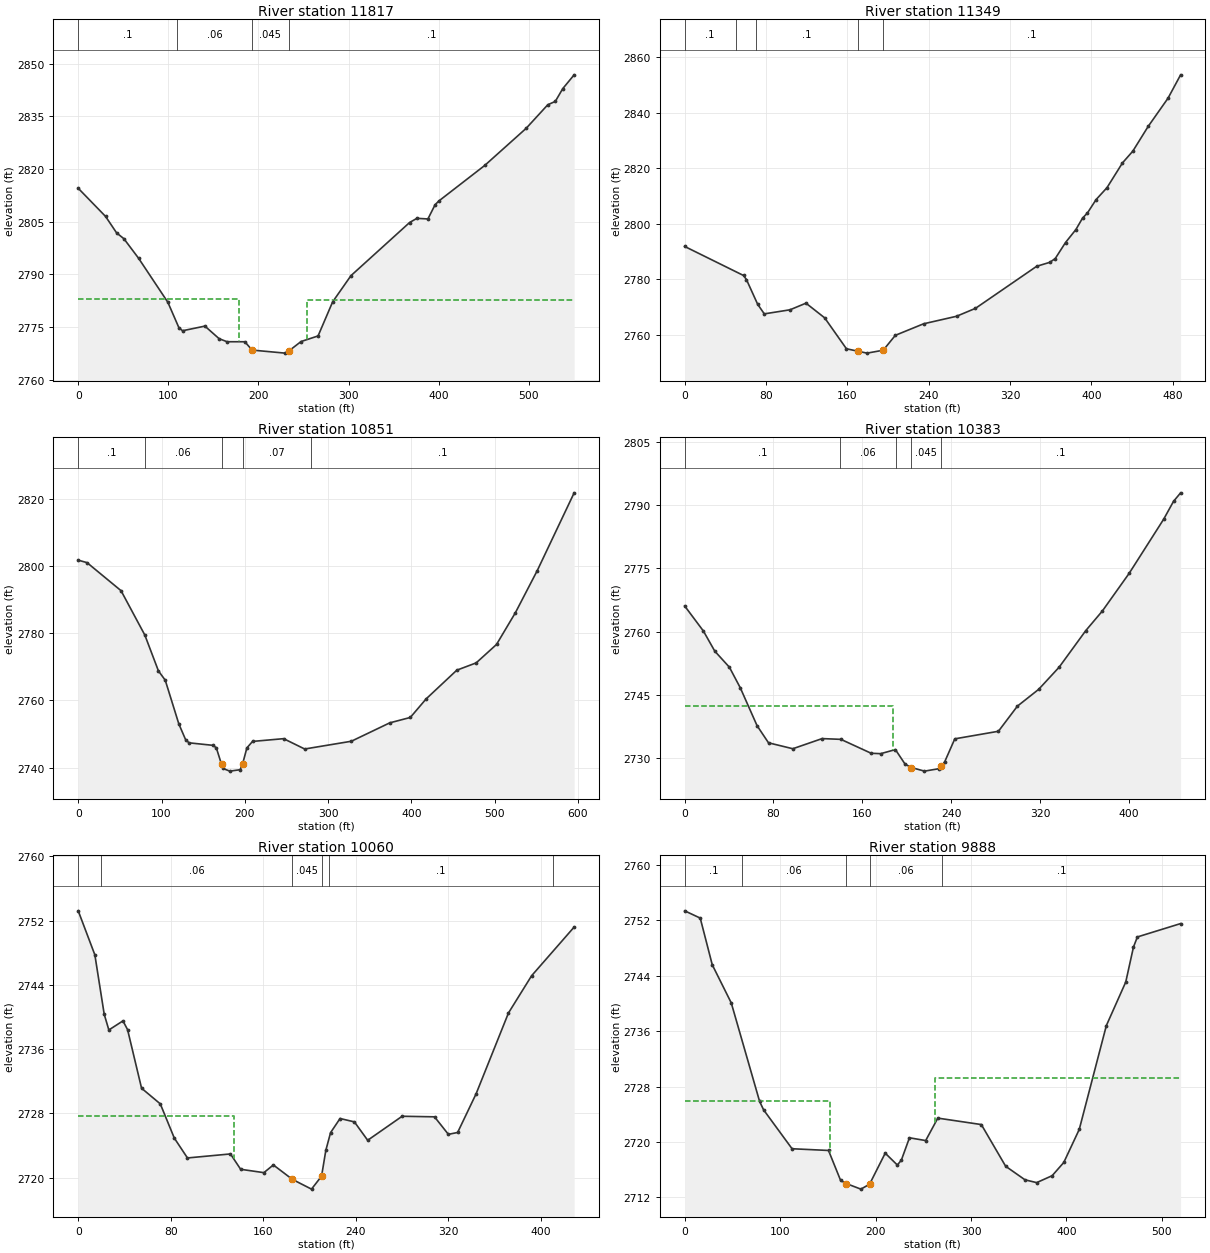
Type RM Length L Ch R = 1 ,11817   ,439.9,467.9,484
XS GIS Cut Line= 3
2229670.24297743531654.5389649042230057.50844109531584.615799498
2230208.24672682531627.882092733
#Sta/Elev= 30
       0 2814.52    30.4 2806.48    42.6  2801.8    50.7 2800.14      67 2794.57
    99.5 2782.02   111.7  2774.8   115.8 2773.91   140.6 2775.23   156.4 2771.64
   165.2 2770.78   184.9 2770.77     193  2768.4   229.6 2767.53   233.5  2768.1
   247.3 2770.83   266.2 2772.43   282.4 2782.16   302.7 2789.61   367.8 2804.76
   375.9 2805.95   388.1 2805.77   396.1 2809.84   400.5 2810.95   451.1 2821.01
   497.1 2831.59   521.1 2838.31   529.5 2839.28   537.8 2842.93   550.4 2846.85
#Mann= 4 ,-1,0
       0      .1       0     110     .06       0     193    .045       0
   233.5      .1       0
#XS Ineff= 2 , 0
          178.21 2782.98  253.69         2782.56
Permanent Ineff=
       F       F
Bank Sta=193,233.5
XS Rating Curve= 0 ,0
Exp/Cntr=0.3,0.1

Type RM Length L Ch R = 1 ,11349   ,483.3,497.6,520.6
XS GIS Cut Line= 3
2229517.25887217 531880.94776189 2229830.6698421532063.977796986
2229907.85529575532162.087017548
#Sta/Elev= 30
       0 2791.89    57.9 2781.43    60.8 2779.93    71.8 2771.06    78.3 2767.61
   103.6 2769.08   119.3 2771.47   137.7 2766.18   159.1 2755.05   170.1 2754.19
   179.4 2753.48   195.3 2754.53   207.2 2759.89     235 2764.04   267.4 2766.75
     286  2769.6   346.2 2784.74   359.1 2786.17   364.5 2787.54   374.6 2793.31
   384.8 2797.98   391.3 2802.07   396.2 2803.97   404.7 2808.78   415.4 2813.06
   430.6 2821.96   440.8 2826.21   455.9 2835.11   475.4 2845.26   487.8 2853.68
#Mann= 5 ,-1,0
       0      .1       0      50     .06       0      70      .1       0
   170.1    .045       0   195.3      .1       0
Bank Sta=170.1,195.3
XS Rating Curve= 0 ,0
Exp/Cntr=0.3,0.1

Type RM Length L Ch R = 1 ,10851   ,486.3,468.2,443.8
XS GIS Cut Line= 3
2229191.23853885531930.8263007372229271.69882846532321.295096897
2229441.93640463532419.948849631
#Sta/Elev= 30
       0 2801.79    10.6 2801.05    51.4  2792.7      80 2779.47    96.3  2768.8
   104.5 2766.02   120.8    2753     129 2748.27   133.1 2747.37   161.9 2746.62
   165.8 2745.88   172.1 2740.93   173.9 2739.73   181.9 2738.94   194.4 2739.36
   197.3 2741.04   202.5 2745.86   209.3 2747.79   246.6 2748.61   271.9 2745.53
   327.9 2747.84     374 2753.32   398.7 2754.93   417.7 2760.46   454.5 2769.01
   477.8 2771.19   502.2 2776.68   524.8 2786.11   551.1 2798.68   595.4 2821.85
#Mann= 5 ,-1,0
       0      .1       0      80     .06       0   172.1    .045       0
   197.3     .07       0     280      .1       0
Bank Sta=172.1,197.3
XS Rating Curve= 0 ,0
Exp/Cntr=0.3,0.1

Type RM Length L Ch R = 1 ,10383   ,300,322.5,341
XS GIS Cut Line= 2
2228859.52419074532415.4542926632229265.94419271532600.786490399
#Sta/Elev= 30
       0 2766.09    16.9 2760.12    27.1 2755.36    40.3 2751.53    50.1 2746.64
    65.2 2737.65    75.5 2733.58    97.4 2732.17   123.8 2734.58   140.7  2734.4
     168 2731.09   176.6    2731   189.8 2731.97   198.5 2728.52   204.1 2727.71
     216 2726.85   229.3 2727.44   231.3 2727.98   234.3 2729.12   243.3 2734.52
   282.6 2736.32   299.7 2742.29   318.8 2746.27   337.3 2751.55   361.2 2760.21
   376.2 2764.89   400.4 2773.86   431.5 2786.73   440.3 2790.94   446.7 2792.97
#Mann= 5 ,-1,0
       0      .1       0     140     .06       0     190      .1       0
   204.1    .045       0   231.3      .1       0
#XS Ineff= 2 , 0
           187.9 2742.27
Permanent Ineff=
       F       F
Bank Sta=204.1,231.3
XS Rating Curve= 0 ,0
Exp/Cntr=0.3,0.1

Type RM Length L Ch R = 1 ,10060   ,158.7,172.3,185.6
XS GIS Cut Line= 4
2228814.29010062532482.9170451312228796.31244901532608.323492783
2228826.32325843532728.2990866222229004.93307132532728.063142351
#Sta/Elev= 30
       0 2753.21    14.4 2747.73    22.5 2740.33    26.5 2738.38    38.7 2739.51
    42.7 2738.42    54.8 2731.13      71 2729.18    83.1 2724.93    94.5 2722.45
   131.7 2722.95   140.5 2721.04   160.6 2720.62   168.8 2721.58   185.3 2719.78
   201.8 2718.57   210.5 2720.18   214.2  2723.4   218.3  2725.6   226.5 2727.36
   238.9 2726.94   250.4 2724.65   280.2 2727.64   308.2 2727.57   320.2 2725.39
   328.2 2725.62   344.2 2730.44   372.2  2740.5   392.2 2745.13     429 2751.19
#Mann= 6 ,-1,0
       0      .1       0      20     .06       0   185.3    .045       0
   210.5     .06       0  216.69      .1       0  410.36     .06       0
#XS Ineff= 2 , 0
          134.41 2727.65
Permanent Ineff=
       F       F
Bank Sta=185.3,210.5
XS Rating Curve= 0 ,0
Exp/Cntr(USF)=0,0
Exp/Cntr=0.3,0.1

Type RM Length L Ch R = 1 ,9888    ,29.4,112.3,133.6
XS GIS Cut Line= 3
2228707.05342961532539.1897536852228602.59527898 532833.74615997
2228637.66943224533037.859381955
#Sta/Elev= 30
       0 2753.36    16.3 2752.31    28.9 2745.57    48.8 2740.07    78.5 2725.85
    82.7 2724.63   112.5 2719.02   150.7 2718.77   163.4 2714.44   169.32713.994
   184.6 2713.19   193.72713.897   210.1 2718.38   222.8 2716.67     227 2717.37
   235.5  2720.6   252.5  2720.2   265.2 2723.44   310.8 2722.51   336.3 2716.49
   356.6 2714.53   368.8 2714.13     385 2715.13   397.2 2717.04   413.4 2721.81
   441.8  2736.8   462.1 2743.08   470.2 2748.13   474.3 2749.59   519.6 2751.52
#Mann= 5 ,-1,0
       0      .1       0      60     .06       0   169.3    .045       0
   193.7     .06       0     270      .1       0
#XS Ineff= 2 , 0
          151.81 2725.95  262.67         2729.21
Permanent Ineff=
       F       F
Bank Sta=169.3,193.7
XS Rating Curve= 0 ,0
Exp/Cntr(USF)=0,0
Exp/Cntr=0.5,0.3

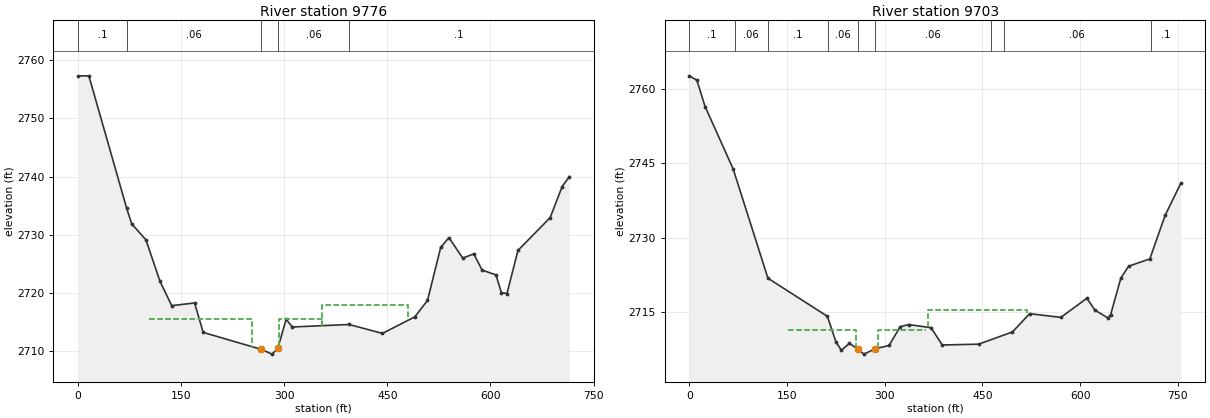
Type RM Length L Ch R = 1 ,9776    ,145.1,72.7,73.7
XS GIS Cut Line= 4
2228672.64436798532530.1504917432228622.13838947532706.304992482
2228323.12538132532834.1252728272228304.23783939533039.706576637
#Sta/Elev= 30
       0 2757.27    15.8 2757.29    70.7 2734.59    78.1 2731.88    98.9 2729.11
   119.3    2722   136.3 2717.82   169.6 2718.29   182.1 2713.23   266.2 2710.33
   282.2  2709.5   290.6 2710.47   302.8 2715.48   311.9 2714.16   394.2 2714.59
   442.9 2713.06   489.9  2715.9   508.4 2718.71   527.6 2727.82   539.6 2729.51
   559.7 2725.98   575.8 2726.72   587.8 2723.93   607.9 2723.11   615.9 2720.08
     624  2719.9     640  2727.3   686.9 2732.95   704.3 2738.28   714.9    2740
#Mann= 5 ,-1,0
       0      .1       0    70.7     .06       0   266.2    .045       0
   290.6     .06       0   394.2      .1       0
#XS Ineff= 3 ,-1
  103.34  253.352715.527  291.72  354.77 2715.61     355     480    2718
Permanent Ineff=
       F       F       F
Bank Sta=266.2,290.6
XS Rating Curve= 0 ,0
Exp/Cntr=0.5,0.3

Type RM Length L Ch R = 1 ,9703    ,171.1,162.7,150.8
XS GIS Cut Line= 4
2228625.58732293 532526.217344212228579.53886611532671.729419134
2228238.73047515 532805.431172512228234.79807064533041.375443174
#Sta/Elev= 30
       0 2762.57    11.5 2761.68    24.1  2756.4    67.2 2743.84   120.6 2721.86
   211.9  2714.2     225 2709.07   233.3 2707.36   245.8 2708.76   258.2 2707.65
     268 2706.59   285.1 2707.65   306.6 2708.33   323.8 2712.11   336.7 2712.53
   371.1 2711.91   388.3 2708.43   444.1 2708.59   496.1 2711.05   522.5 2714.73
   570.5 2713.98   610.5 2717.84   622.5 2715.48   642.5 2713.87   646.9 2714.53
   662.5 2721.86   674.5 2724.28   707.1 2725.74   730.5 2734.49   754.7 2740.97
#Mann= 9 ,-1,0
       0      .1       0      70     .06       0     120      .1       0
  212.62     .06       0   258.2    .045       0   285.1     .06       0
  462.62      .1       0  482.62     .06       0  708.72      .1       0
#XS Ineff= 3 ,-1
  151.64   256.62711.418  289.97  363.992711.419  366.21  518.59 2715.44
Permanent Ineff=
       F       F       F
Bank Sta=258.2,285.1
XS Rating Curve= 0 ,0
Exp/Cntr(USF)=0,0
Exp/Cntr=0.5,0.3