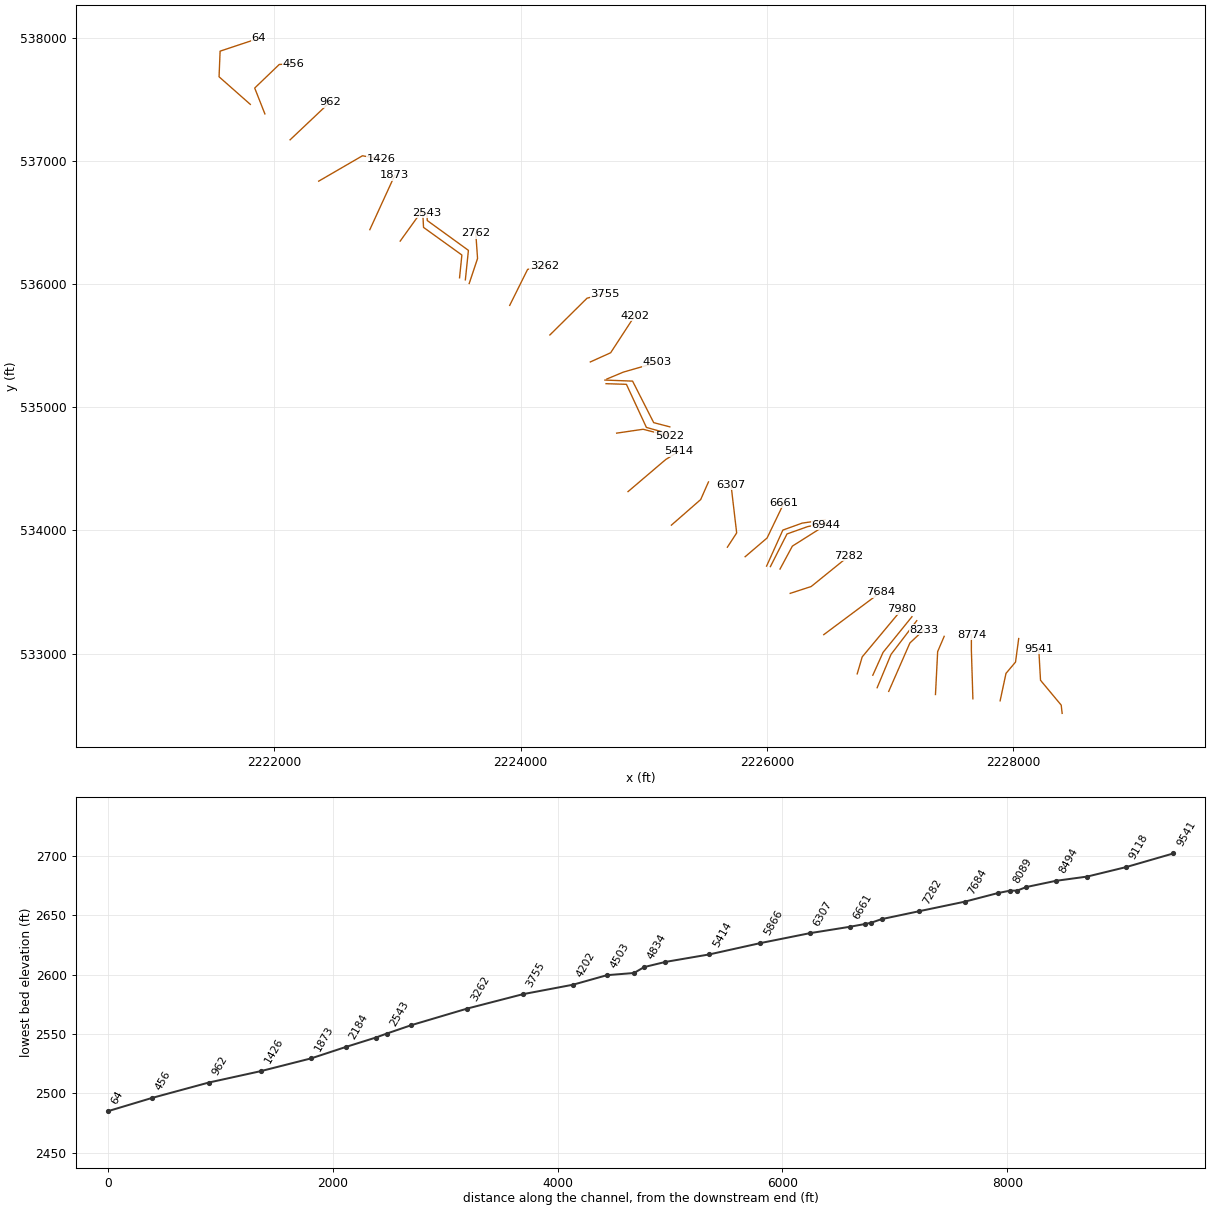
HEC-RAS study DRYFK.prj: DRYFK

--- DRYFK.g01 (geometry) --- (continued)

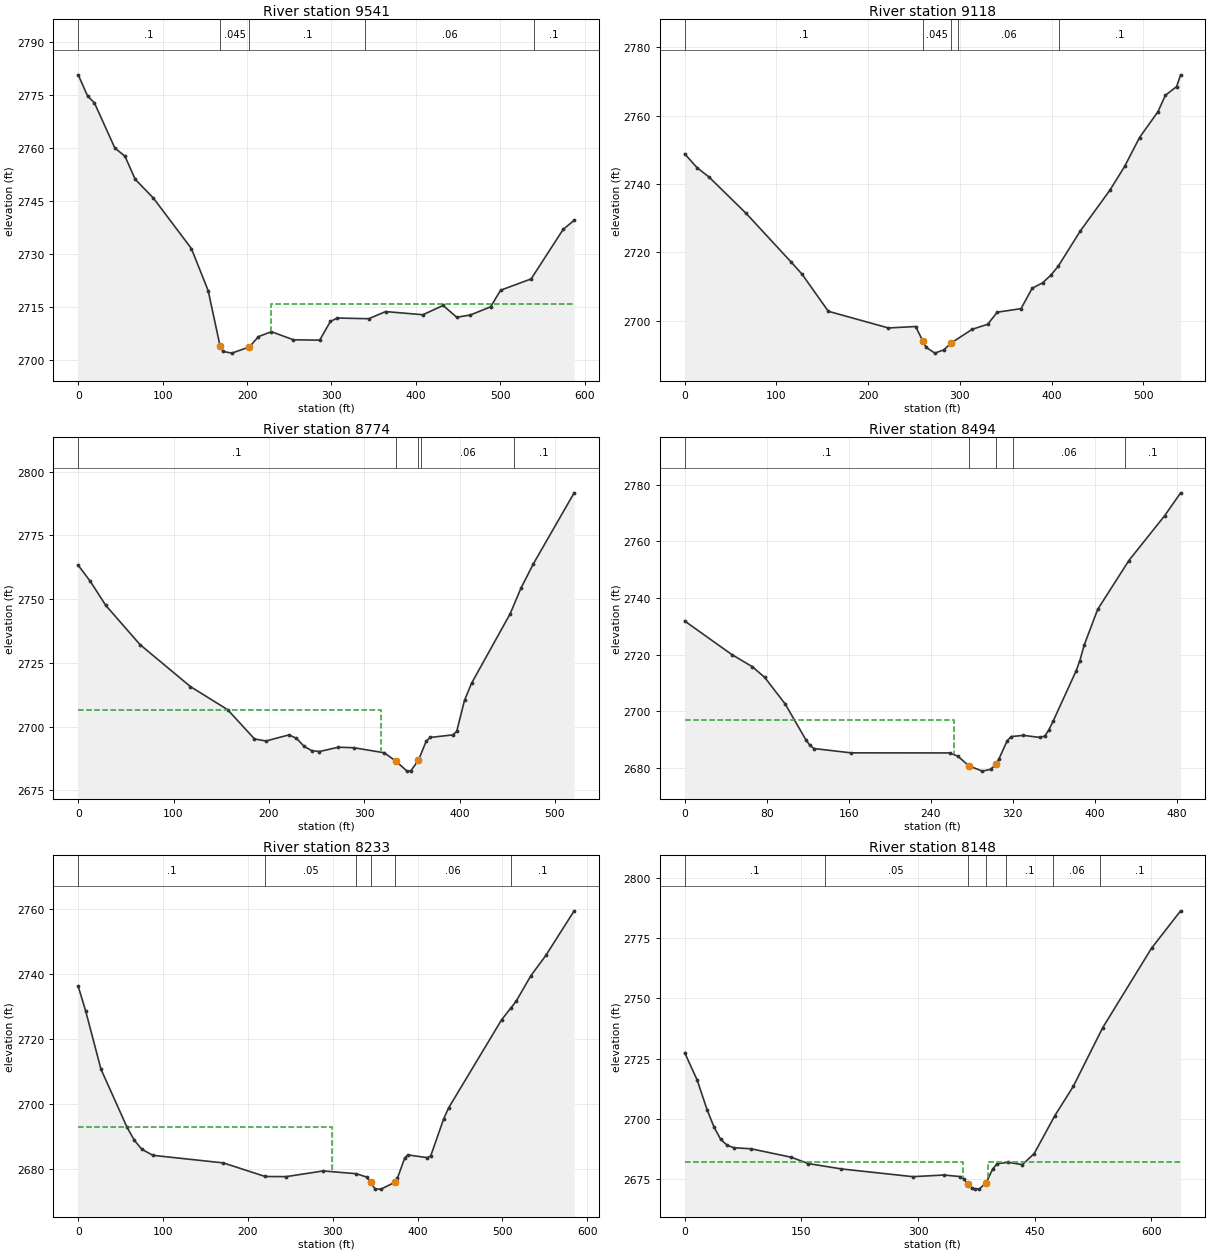
Type RM Length L Ch R = 1 ,9541    ,450.4,422.3,376.8
XS GIS Cut Line= 4
2228397.59825168532514.100483304 2228389.9967619532581.043645698
2228221.99457563532782.9335720132228207.44317256533040.078587098
#Sta/Elev= 30
       0 2780.84    11.1 2774.85    19.2  2772.9    43.4 2760.13    55.4  2757.8
    67.5 2751.28      89 2745.98   134.1 2731.67     154 2719.74   168.2 2703.95
   171.6 2702.55     182 2702.07   202.8 2703.82   213.6 2706.75   228.9 2708.14
   254.9 2705.85   286.1 2705.74   298.8 2711.04   306.9    2712   344.3 2711.81
   364.2 2713.83   408.4 2712.94   432.4 2715.56   448.5 2712.22   464.5 2712.86
   488.5 2715.16   500.5 2719.88   536.6 2723.07   574.6  2737.1   587.6 2739.66
#Mann= 5 ,-1,0
       0      .1       0   168.2    .045       0   202.8      .1       0
  340.02     .06       0  540.02      .1       0
#XS Ineff= 2 , 0
                          228.92         2716.08
Permanent Ineff=
       F       F
Bank Sta=168.2,202.8
XS Rating Curve= 0 ,0
Exp/Cntr=0.3,0.1

Type RM Length L Ch R = 1 ,9118    ,330.2,344.2,362.7
XS GIS Cut Line= 4
2227893.90233006532616.0214608932227941.62564777532839.160216701
2228019.01481164532930.7373939412228044.81119959533121.630664806
#Sta/Elev= 30
       0 2748.85    13.5 2744.79    26.5 2742.07    66.9 2731.45   115.7 2717.28
     128 2713.61   156.6 2702.76   222.1 2697.88   251.8  2698.3   259.8 2693.97
   263.1 2692.25   272.7 2690.51   282.5 2691.46   290.82693.531   313.7 2697.51
   330.3 2698.95   340.8  2702.5   366.7 2703.53   378.8 2709.48   390.4 2711.13
     399 2713.28   407.1 2715.89   431.3 2726.26   463.6 2738.21   479.7 2745.19
   495.9 2753.63     516 2761.19   524.1 2765.99   536.3 2768.53   540.7 2771.98
#Mann= 5 ,-1,0
       0      .1       0   259.8    .045       0   290.8      .1       0
  298.19     .06       0  408.08      .1       0
Bank Sta=259.8,290.8
XS Rating Curve= 0 ,0
Exp/Cntr(USF)=0,0
Exp/Cntr=0.3,0.1

Type RM Length L Ch R = 1 ,8774    ,281.8,280.2,277.9
XS GIS Cut Line= 3
 2227672.7490793532632.4175028352227660.44782003533029.618598553
2227660.77986469533152.442887972
#Sta/Elev= 30
       0 2763.32    12.8 2756.96    28.8 2747.63    64.8 2732.21   117.7 2715.73
   156.8 2706.66   184.9  2695.2   196.9 2694.39   220.9 2696.77   228.9 2695.46
   236.9  2692.3   244.9 2690.61   252.9 2690.26   272.9 2691.95   288.9 2691.76
   320.9 2689.78   332.9 2686.58   344.9 2682.57   348.9 2682.71   356.9 2686.85
   364.9 2694.24   368.9 2695.77   392.9 2696.78     397 2698.15   405.2 2710.35
   412.6 2717.05     453 2744.24   464.5 2754.41   477.4 2763.88   520.2 2791.73
#Mann= 5 ,-1,0
       0      .1       0   332.9    .045       0   356.9      .1       0
     360     .06       0  457.39      .1       0
#XS Ineff= 2 , 0
          317.85 2706.72
Permanent Ineff=
       F       F
Bank Sta=332.9,356.9
XS Rating Curve= 0 ,0
Exp/Cntr=0.3,0.1

Type RM Length L Ch R = 1 ,8494    ,268.2,260.5,250.9
XS GIS Cut Line= 3
2227368.90717756532667.1997280132227386.60017341533015.751746332
2227439.67916097533139.602717308
#Sta/Elev= 30
       0 2731.92      46 2720.08      66 2715.79    78.1 2712.01    98.1 2702.61
   118.1 2690.09   122.1  2688.1   126.1 2686.93   162.2 2685.41   258.3 2685.38
   266.3 2684.26   277.22680.811   290.4 2678.96   298.4 2679.59   303.52681.336
   306.4 2683.17   314.4  2689.6   318.4 2691.15   330.4 2691.57   346.4 2690.85
   351.3 2691.36   354.9 2693.33   359.3 2696.55   381.8 2714.34   385.4 2717.95
   389.7 2723.48   402.8 2736.02   433.2 2753.24   468.1 2769.06   483.7 2777.14
#Mann= 5 ,-1,0
       0      .1       0   277.2    .045       0   303.5      .1       0
     320     .06       0     429      .1       0
#XS Ineff= 2 , 0
          262.55 2697.09
Permanent Ineff=
       F       F
Bank Sta=277.2,303.5
XS Rating Curve= 0 ,0
Exp/Cntr(USF)=0,0
Exp/Cntr=0.3,0.1

Type RM Length L Ch R = 1 ,8233    ,89.4,84.9,78.5
XS GIS Cut Line= 3
2226989.17136557532692.5952186382227161.16983775533085.705563001
2227274.49084903533192.088336103
#Sta/Elev= 30
       0 2736.23     8.8 2728.62    26.8 2710.71    57.4 2692.91    66.1 2688.82
    74.9 2686.06      88 2684.18   170.9 2681.85   220.4 2677.66   245.1 2677.62
   288.8 2679.37   327.7 2678.52   339.9 2677.49   344.6 2675.83   349.9 2673.82
   356.8 2673.77   373.3 2675.88   376.3 2677.21   384.9  2683.4   388.5 2684.31
   411.1 2683.47   415.4 2683.97   430.8 2695.45   436.5 2698.77     499 2725.92
     510 2729.57     516 2731.57   533.5  2739.5   551.1 2745.71   584.5 2759.46
#Mann= 6 ,-1,0
       0      .1       0   220.4     .05       0   327.7     .06       0
   344.6    .045       0   373.3     .06       0     510      .1       0
#XS Ineff= 2 , 0
           298.8 2692.91
Permanent Ineff=
       F       F
Bank Sta=344.6,373.3
XS Rating Curve= 0 ,0
Exp/Cntr=0.5,0.3

Type RM Length L Ch R = 1 ,8148    ,62.4,59.8,59.1
XS GIS Cut Line= 3
2226895.29778563532722.4331378022227008.19987021532993.395227895
2227216.95714672533266.883442862
#Sta/Elev= 30
       0 2727.44      16  2716.1      29 2703.54    37.6 2696.61    46.3 2691.37
      55 2688.84    63.6  2687.9    85.3 2687.47   137.2 2683.94   158.8 2681.32
   201.6 2679.09   293.5 2675.87   333.3 2676.56   353.7 2675.92   358.7 2674.98
   363.7 2672.87   368.8 2671.22   373.8 2670.69     379 2670.81   387.5 2673.34
   396.1 2679.13   401.8 2681.29   416.1 2681.83   434.2 2680.88   449.3 2685.46
     476 2701.31   499.6 2713.42   537.4 2737.81   600.2 2770.89   637.6 2786.43
#Mann= 7 ,-1,0
       0      .1       0     180     .05       0   363.7    .045       0
   387.5     .05       0  413.54      .1       0  473.54     .06       0
  533.54      .1       0
#XS Ineff= 2 , 0
          357.49 2681.89  390.39         2681.78
Permanent Ineff=
       F       F
Bank Sta=363.7,387.5
XS Rating Curve= 0 ,0
Exp/Cntr(USF)=0,0
Exp/Cntr=0.5,0.3

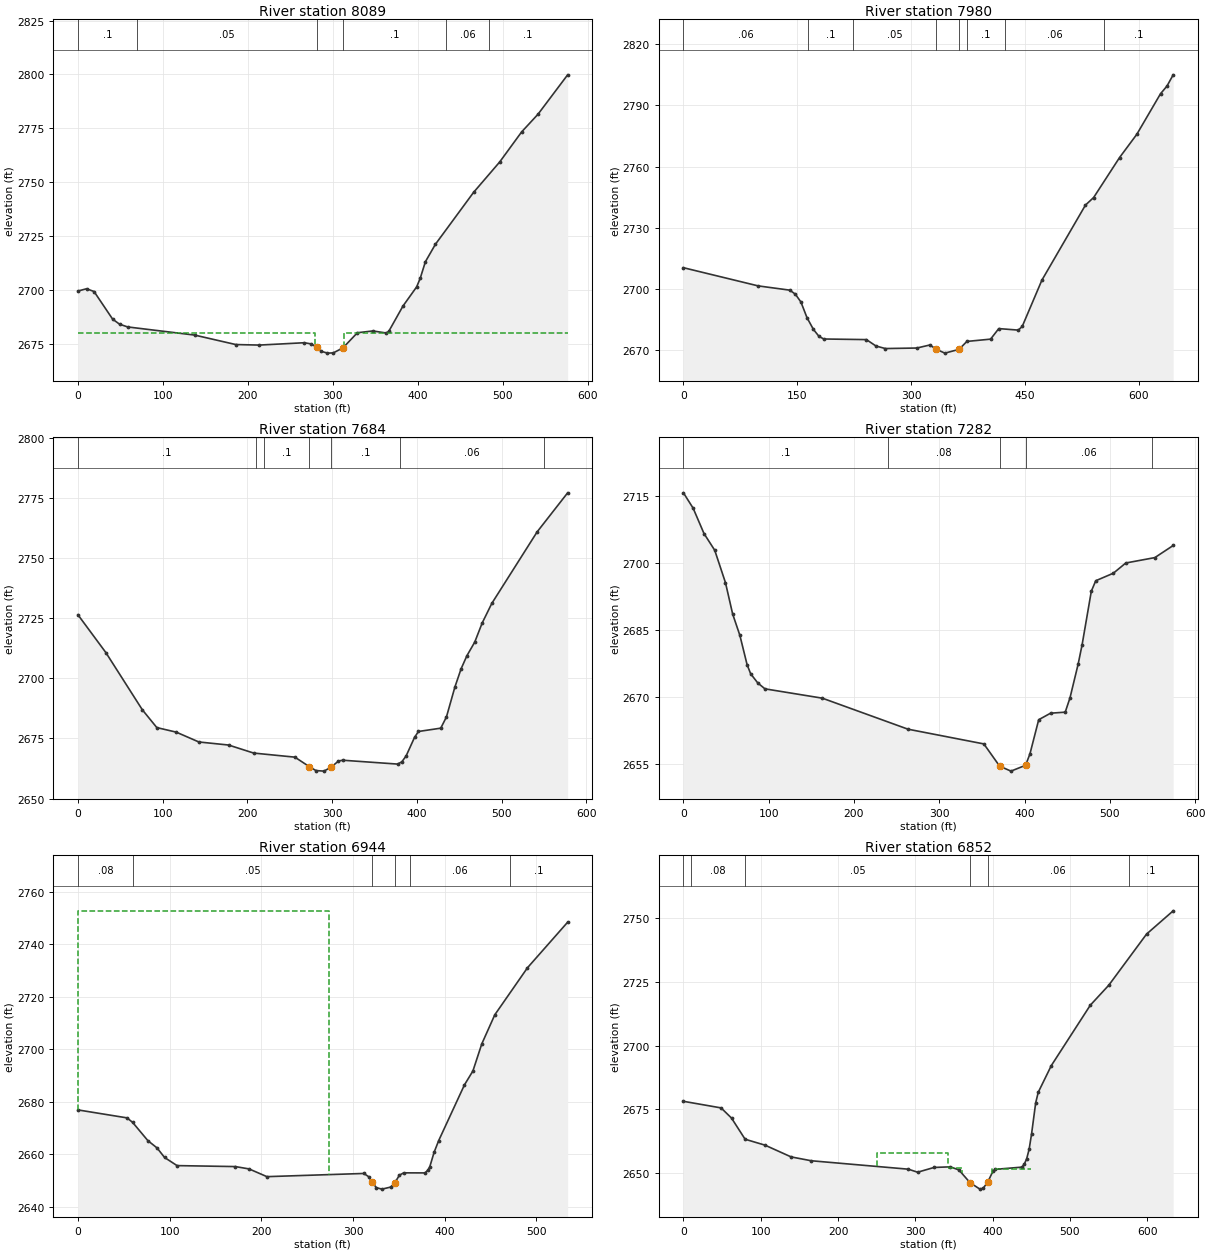
Type RM Length L Ch R = 1 ,8089    ,108.7,109,108.2
XS GIS Cut Line= 3
 2226860.0906282532823.8406259832226943.46893175533009.577962508
2227178.11858365533299.248912088
#Sta/Elev= 30
       0 2699.53    10.2 2700.58      19 2699.31    40.9 2686.48      49 2684.16
    58.5 2682.88   137.4  2679.1   185.8 2674.71   213.4 2674.46   266.4 2675.55
   274.9 2674.98     281  2673.4   286.3  2671.6   293.7 2670.73   300.5 2670.84
   311.9 2673.14   328.9 2680.18   347.2 2681.02   363.1 2680.05   365.9 2680.85
   382.6 2692.58   398.7 2701.46   402.9 2705.45     409 2713.14   420.8 2721.24
   465.6 2745.25   496.5 2759.43   522.3 2773.36   541.5 2781.53   576.4 2799.81
#Mann= 6 ,-1,0
       0      .1       0      70     .05       0     281    .045       0
   311.9      .1       0  433.59     .06       0  483.59      .1       0
#XS Ineff= 2 ,-1
       0  278.96    2680  313.41576.3799    2680
Permanent Ineff=
       F       F
Bank Sta=281,311.9
XS Rating Curve= 0 ,0
Exp/Cntr(USF)=0,0
Exp/Cntr=0.5,0.3

Type RM Length L Ch R = 1 ,7980    ,299.6,295.2,288.8
XS GIS Cut Line= 3
2226733.23965189532834.7939919252226773.96287804532972.839918389
2227094.95998385533358.023192714
#Sta/Elev= 30
       0 2710.49    98.4 2701.59   140.1  2699.5   147.4 2697.55   154.8  2693.7
   162.8 2686.03   171.3 2680.26   178.6 2676.87   184.9 2675.59   241.1 2675.29
   253.7 2672.15   266.1 2670.91   307.6 2671.17   324.7 2672.66   333.2 2670.53
   344.5 2668.67   363.1 2670.51   373.5  2674.4   404.7 2675.52   415.5 2680.68
   441.2 2679.94   446.4 2681.74   472.3 2704.39   529.7 2741.14   540.5 2744.86
   574.6  2764.4   597.4 2775.81   628.6 2795.65   637.1 2799.41   645.3 2804.92
#Mann= 8 ,-1,0
       0     .06       0  163.93      .1       0  223.93     .05       0
   333.2    .045       0   363.1     .05       0  373.93      .1       0
  423.93     .06       0  553.93      .1       0
Bank Sta=333.2,363.1
XS Rating Curve= 0 ,0
Exp/Cntr=0.3,0.1

Type RM Length L Ch R = 1 ,7684    ,398.6,403,401.7
XS GIS Cut Line= 2
2226461.73411761533153.3144977272226924.95990124533498.686020273
#Sta/Elev= 30
       0 2726.53      33 2710.77      76 2686.96    93.1 2679.54     116 2677.65
   142.7 2673.55   177.7 2672.28   207.4 2668.93     256 2667.23   273.2 2663.23
   280.8 2661.65   290.3 2661.41   298.9  2663.1   307.4 2665.61   312.4 2665.95
   377.3 2664.34   382.2 2665.31   387.2 2667.71   397.2 2675.49   401.8 2677.92
   428.1  2679.3   434.8 2683.97   444.7 2696.34   452.1 2704.03     459  2709.5
   468.2 2715.15     477 2723.12   488.3 2731.24   541.8 2761.04   577.8  2777.3
#Mann= 7 ,-1,0
       0      .1       0     210     .05       0     220      .1       0
   273.2    .045       0   298.9      .1       0     380     .06       0
     550      .1       0
Bank Sta=273.2,298.9
XS Rating Curve= 0 ,0
Exp/Cntr(USF)=0,0
Exp/Cntr=0.3,0.1

Type RM Length L Ch R = 1 ,7282    ,339.8,337,334.4
XS GIS Cut Line= 3
2226189.29282038533488.6560565232226359.73526234 533544.32288193
2226666.74416986533792.822317797
#Sta/Elev= 30
       0 2715.73    11.4 2712.28    24.1 2706.62    36.7 2702.87    49.3 2695.61
    57.7 2688.61    66.2 2683.81    74.6 2677.29    78.8 2675.23    87.2 2673.16
    95.6 2671.85   162.9 2669.76   263.3 2662.82   352.3 2659.52   370.8 2654.54
   384.1 2653.43   401.2 2654.74   406.3 2657.27   416.6 2664.94   430.5  2666.4
   447.7 2666.63   453.3 2669.84   462.9 2677.42   467.5 2681.72   478.3  2693.7
   483.5 2696.05   504.1 2697.73   518.7 2700.02   552.8 2701.23   574.3 2703.94
#Mann= 5 ,-1,0
       0      .1       0   239.3     .08       0   370.8    .045       0
   401.2     .06       0   549.3      .1       0
Bank Sta=370.8,401.2
XS Rating Curve= 0 ,0
Exp/Cntr=0.3,0.1

Type RM Length L Ch R = 1 ,6944    ,96.4,92.5,86.2
XS GIS Cut Line= 3
 2226106.5189351533685.9450653172226206.79525013533872.341039141
2226479.31088275534044.580356725
#Sta/Elev= 30
       0 2676.88    53.6 2673.84    59.7 2672.11    76.3 2665.17    86.3 2662.39
    94.5 2658.76   108.1 2655.66   171.7 2655.29   186.7 2654.39   206.1 2651.45
   311.8 2652.67   317.4 2651.35   320.5 2649.46   325.5 2647.24   331.6  2646.7
   341.1 2647.49   345.8 2649.21   350.5    2652   355.2  2652.9   378.5 2652.88
   381.4 2653.86   383.6 2655.13   388.4 2660.74   393.4  2665.2   421.5 2686.43
   430.7 2691.71   440.4 2702.05   454.6 2713.13   490.2 2731.03     534 2748.39
#Mann= 6 ,-1,0
       0     .08       0      60     .05       0   320.5    .045       0
   345.8     .05       0  361.66     .06       0  471.66      .1       0
#XS Ineff= 2 , 0
          273.73 2752.72
Permanent Ineff=
       F       F
Bank Sta=320.5,345.8
XS Rating Curve= 0 ,0
Exp/Cntr(USF)=0,0
Exp/Cntr=0.5,0.3

Type RM Length L Ch R = 1 ,6852    ,53,50.8,51
XS GIS Cut Line= 4
2226028.34562496533705.7648879662226163.13584903533971.118065113
2226331.23815709534030.8366029592226485.96970316534061.321153851
#Sta/Elev= 30
       0 2678.17    48.7 2675.58    62.2 2671.59    79.8 2663.27   105.6 2660.94
   139.3 2656.33   165.3 2654.82   291.1  2651.5     303 2650.31   324.2 2652.18
   345.4 2652.43   356.4 2651.21   370.9  2646.2   383.6 2643.67   387.9 2644.03
     394 2646.56   400.3 2650.63   403.4 2651.44   437.9 2652.31     441 2653.44
   444.1 2655.57   447.3 2659.33   450.4 2665.22   455.8 2677.59   459.1 2681.71
     476  2692.2   526.5 2715.94   550.4 2723.79   599.3 2743.88   633.7    2753
#Mann= 6 ,-1,0
       0     .06       0      10     .08       0      80     .05       0
   370.9    .045       0     394     .06       0  576.02      .1       0
#XS Ineff= 3 ,-1
     250     342    2658     342     360    2652     399     450  2651.7
Permanent Ineff=
       F       F       F
Bank Sta=370.9,394
XS Rating Curve= 0 ,0
Exp/Cntr=0.5,0.3

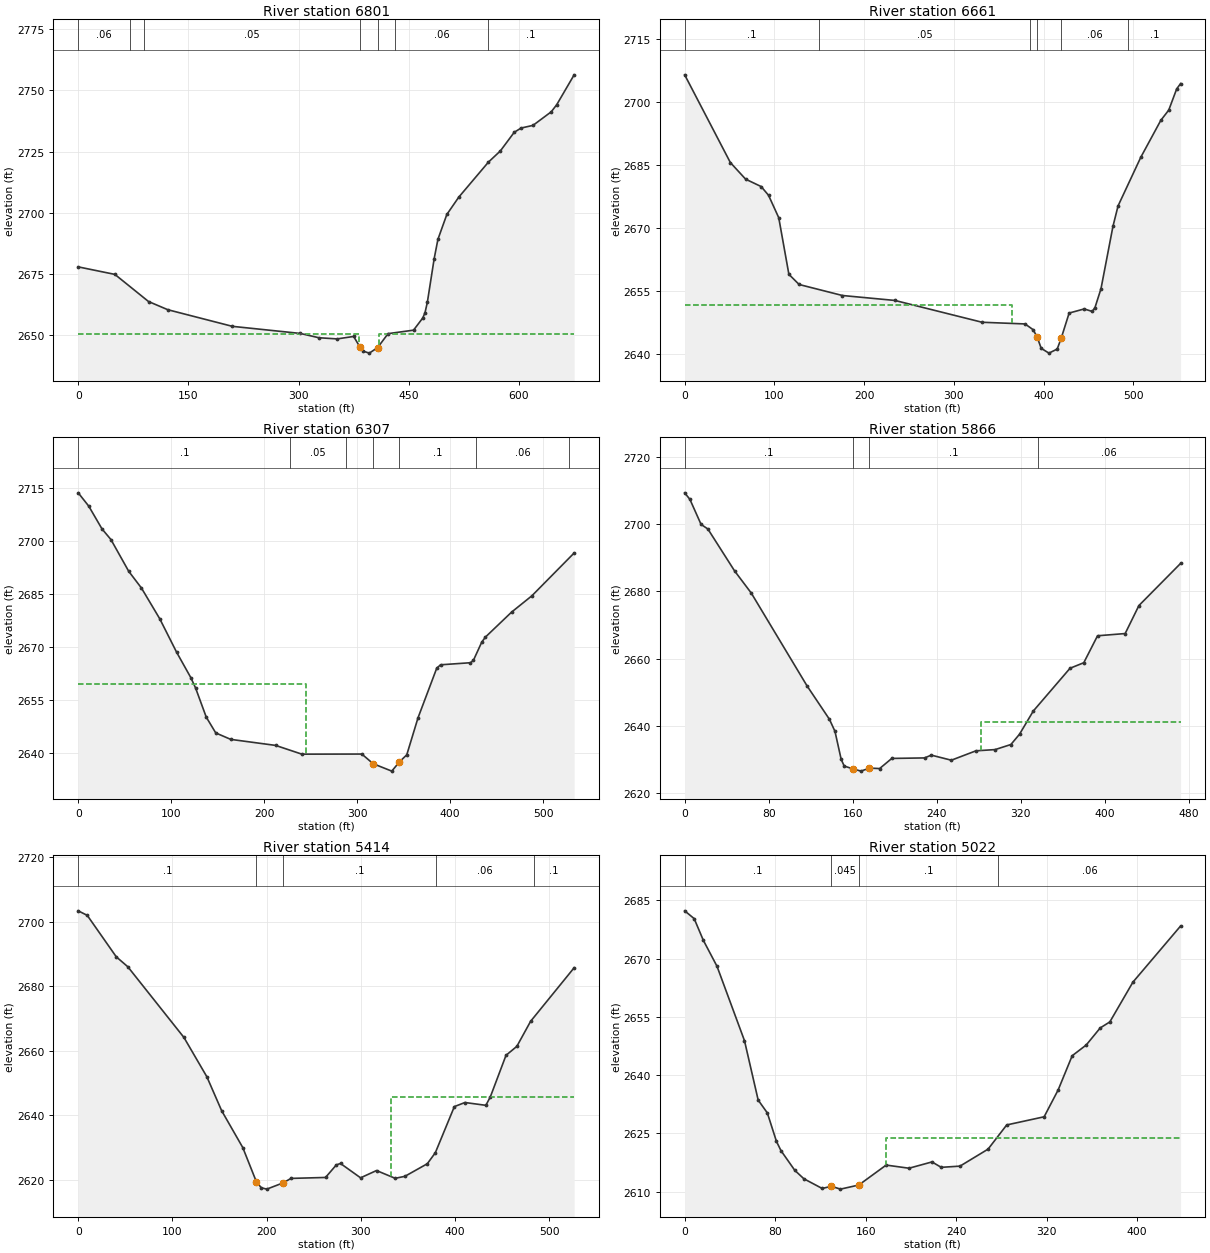
Type RM Length L Ch R = 1 ,6801    ,122,139.7,157.9
XS GIS Cut Line= 4
 2225997.3770141533709.9523948562226129.50580567534002.523290479
2226286.40874566534059.1499154382226471.62499813534086.283506564
#Sta/Elev= 30
       0  2677.9    49.9 2674.83    95.7 2663.75     122  2660.4   209.8 2653.62
     302 2650.73   327.7 2648.96   352.4 2648.49   374.9 2649.49   383.4 2645.18
   387.8 2643.49   396.2 2642.68   407.5 2644.93   421.7 2650.63   456.4 2652.06
   468.9 2657.01     472 2659.18   475.2 2663.44   484.5 2681.29   489.6 2689.16
   501.7 2699.29   517.9 2706.35   558.3 2720.67   574.5 2725.22   593.4 2732.84
   602.8 2734.59     619 2735.68   643.8 2741.22   651.3 2744.13     675 2756.32
#Mann= 7 ,-1,0
       0     .06       0      70      .1       0      90     .05       0
   383.4    .045       0   407.5     .05       0  431.02     .06       0
  557.83      .1       0
#XS Ineff= 2 , 0
          382.72  2650.5  409.82         2650.41
Permanent Ineff=
       F       F
Bank Sta=383.4,407.5
XS Rating Curve= 0 ,0
Exp/Cntr(USF)=0,0
Exp/Cntr=0.5,0.3

Type RM Length L Ch R = 1 ,6661    ,341.4,354.8,368.3
XS GIS Cut Line= 3
2225823.38581031533786.2213803482226001.52373466533938.405434926
  2226139.551133534225.077723782
#Sta/Elev= 30
       0 2706.51    50.9 2685.62    67.9 2681.67    85.2 2679.91    93.4 2677.84
   104.8 2672.49   116.1 2659.01   127.5 2656.59   175.7 2653.97   234.3 2652.79
   331.3  2647.6   379.2  2647.2   388.3 2645.81   392.8    2644   397.2 2641.39
   405.8 2640.25     415 2641.22   419.4 2643.75   428.3 2649.79   445.1 2650.77
   454.1 2650.17   457.1  2651.1   463.8 2655.59   477.1 2670.41   482.8  2675.3
   508.2 2686.91   530.4 2695.66   539.3 2698.12   548.1 2703.15   552.5 2704.44
#Mann= 6 ,-1,0
       0      .1       0     150     .05       0  384.29     .06       0
   392.8    .045       0   419.4     .06       0  494.29      .1       0
#XS Ineff= 2 , 0
          365.12 2651.62
Permanent Ineff=
       F       F
Bank Sta=392.8,419.4
XS Rating Curve= 0 ,0
Exp/Cntr(USF)=0,0
Exp/Cntr=0.3,0.1

Type RM Length L Ch R = 1 ,6307    ,451.5,440.3,417
XS GIS Cut Line= 3
2225679.08924662533863.7101538752225754.43850126533979.412285447
2225708.40066345534371.977818825
#Sta/Elev= 30
       0 2713.77    11.3 2710.01    25.6 2703.53    35.2 2700.52    54.3 2691.53
      68 2686.78    87.7 2678.06   105.9 2668.54   121.1 2661.38   126.2 2658.45
   137.7 2650.18   147.9 2645.71     164 2643.88   212.3 2642.17   240.5 2639.69
     305 2639.72   317.1 2636.99   337.2 2634.88   345.3 2637.47   353.3  2639.5
   365.4 2649.99   385.5 2664.04   389.6 2665.02   421.8 2665.61   424.9 2666.24
   433.9 2671.43   437.9 2672.88     466 2679.95   487.8 2684.57   533.3 2696.72
#Mann= 7 ,-1,0
       0      .1       0  228.07     .05       0  288.07      .1       0
   317.1    .045       0   345.3      .1       0  428.07     .06       0
  528.07      .1       0
#XS Ineff= 2 , 0
          245.16 2659.52
Permanent Ineff=
       F       F
Bank Sta=317.1,345.3
XS Rating Curve= 0 ,0
Exp/Cntr=0.3,0.1

Type RM Length L Ch R = 1 ,5866    ,453.1,452.4,449.9
XS GIS Cut Line= 3
2225224.42214786534042.6624110182225462.31401253534250.595904756
2225525.51829324534393.538175452
#Sta/Elev= 30
       0 2709.34       5 2707.38    15.6 2699.95    22.1 2698.57    47.5 2686.11
    63.4 2679.51   116.5 2651.89   137.8 2641.96   143.1 2638.36     149 2630.03
   151.9 2628.03   160.4 2627.17   167.9 2626.52   175.92627.427   185.6 2627.28
   197.2  2630.3   228.4 2630.45   234.8 2631.28   253.9 2629.77   277.3 2632.56
   295.6 2632.93   310.6 2634.44   318.8  2637.5   331.9 2644.39   366.9 2657.13
     380 2658.78   393.1  2666.8   419.4 2667.46   432.5  2675.8   472.2 2688.34
#Mann= 4 ,-1,0
       0      .1       0   160.4    .045       0   175.9      .1       0
  335.96     .06       0
#XS Ineff= 2 , 0
                          281.68          2641.1
Permanent Ineff=
       F       F
Bank Sta=160.4,175.9
XS Rating Curve= 0 ,0
Exp/Cntr=0.3,0.1

Type RM Length L Ch R = 1 ,5414    ,400.7,391.6,373.7
XS GIS Cut Line= 3
2224872.24425502534314.985445259 2225179.2993548534576.346606629
2225283.90104437534641.032799555
#Sta/Elev= 30
       0 2703.39     9.6 2701.98    40.4 2689.11    52.6 2686.04   112.2 2664.08
   136.5 2651.89   152.2 2641.35   174.6 2629.92     189 2619.33   194.3 2617.43
   200.1 2617.02   217.2 2618.94   225.8 2620.35   262.4 2620.64   273.9 2624.55
   278.3 2624.98   299.6 2620.53   316.5 2622.79   336.3 2620.38   346.6 2620.99
   370.4  2624.9   378.9 2628.31   399.1 2642.63   410.3  2643.9   432.5 2643.03
   437.2  2645.6   453.9 2658.55   465.4 2661.33     480  2669.1   526.2 2685.73
#Mann= 5 ,-1,0
       0      .1       0     189    .045       0   217.2      .1       0
     380     .06       0  483.23      .1       0
#XS Ineff= 2 , 0
                           331.8         2645.66
Permanent Ineff=
       F       F
Bank Sta=189,217.2
XS Rating Curve= 0 ,0
Exp/Cntr=0.3,0.1

Type RM Length L Ch R = 1 ,5022    ,216.7,188.3,156.4
XS GIS Cut Line= 3
2224779.83883597534789.8644923372224994.90994281534821.341109654
2225208.99680813534765.631128186
#Sta/Elev= 30
       0  2682.3     8.4 2680.29    16.5 2674.71    28.6 2668.02    52.9 2648.87
      65 2633.59    73.1 2630.28    81.2 2622.93    85.2 2620.56    97.4  2615.5
   105.4 2613.34   121.6 2610.84   129.7  2611.4   137.8 2610.67     154 2611.73
   178.2 2616.86   198.4 2616.05   218.7 2617.67   226.9 2616.28   243.5 2616.59
   268.3 2620.96   284.8 2627.19   317.9 2629.29   330.3  2636.2   342.7    2645
   355.1 2647.76   367.5 2652.16     376 2653.71   396.4 2663.94   438.6  2678.4
#Mann= 4 ,-1,0
       0      .1       0   129.7    .045       0     154      .1       0
  277.36     .06       0
#XS Ineff= 1 ,-1
  177.66438.5789 2623.89
Permanent Ineff=
       F
Bank Sta=129.7,154
XS Rating Curve= 0 ,0
Exp/Cntr(USF)=0,0
Exp/Cntr=0.5,0.3

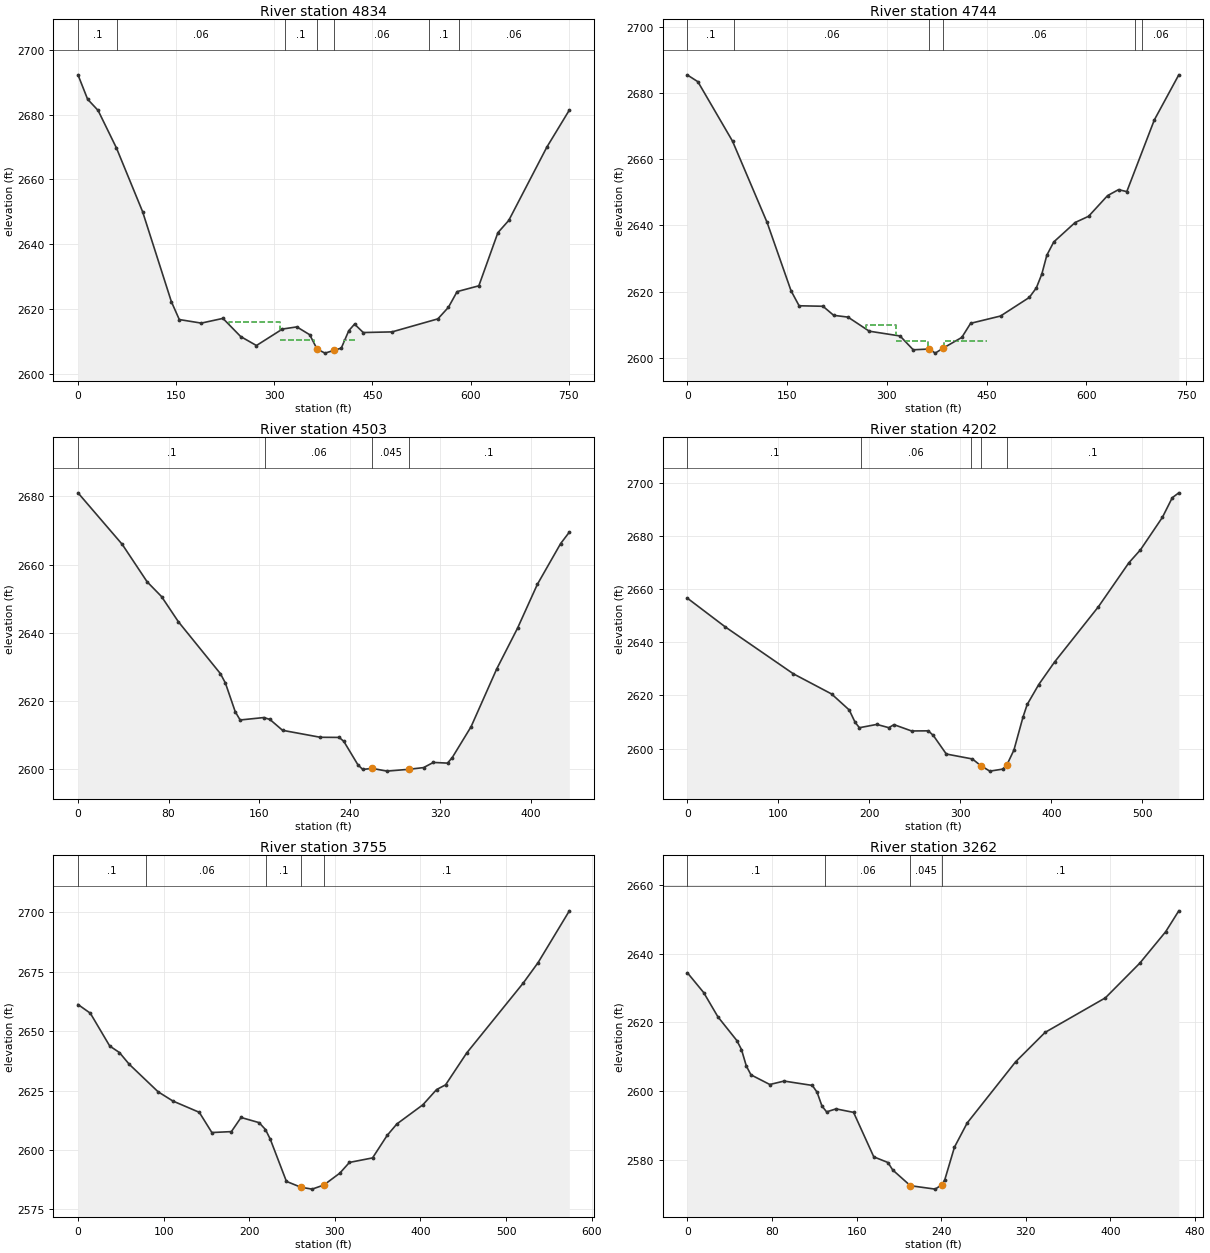
Type RM Length L Ch R = 1 ,4834    ,100.5,90.4,93.8
XS GIS Cut Line= 4
2224693.49859201535191.405225559 2224859.1669112535186.228723955
2225021.38587952534836.3175447792225213.26691159534782.344520909
#Sta/Elev= 30
       0 2692.29    14.7 2684.76    30.7  2681.3    58.7 2669.73    98.7 2650.04
   142.7 2622.23   154.8 2616.71   188.4 2615.61   221.5 2617.07   248.6 2611.46
   272.7 2608.69   312.4 2613.78   334.4 2614.44   354.1 2612.02   365.3  2607.6
   377.4 2606.34   391.8 2607.23   402.3 2607.89   413.8 2613.28   422.6  2615.3
   435.9  2612.7   479.9  2612.9   549.9 2616.92     566 2620.49   579.3 2625.34
   612.5 2627.13   641.6 2643.54   658.2 2647.32   716.4 2669.96   750.8 2681.41
#Mann= 7 ,-1,0
       0      .1       0      60     .06       0  315.75      .1       0
   365.3    .045       0   391.8     .06       0  535.75      .1       0
  581.43     .06       0
#XS Ineff= 3 ,-1
     230     308    2616     308   360.9  2610.3   405.9     423  2610.3
Permanent Ineff=
       F       F       F
Bank Sta=365.3,391.8
XS Rating Curve= 0 ,0
Exp/Cntr=0.5,0.3

Type RM Length L Ch R = 1 ,4744    ,203.7,241,274.4
XS GIS Cut Line= 4
2224684.43707076535220.7610613472224909.32263346535212.259989275
2225080.60283758534875.1027048272225211.77251569534840.890785581
#Sta/Elev= 30
       0 2685.51    15.7 2683.49    67.8  2665.5   119.8  2640.9   155.8 2620.23
   167.9 2615.69   203.8 2615.54   219.9  2612.8   241.4 2612.26   273.4    2608
   319.7 2606.55   339.5 2602.37   363.8  2602.6   372.6 2601.36   384.2 2602.84
   412.5 2606.11   425.8 2610.38   470.8 2612.59     514 2618.21   524.6 2621.09
   532.9 2625.32   540.4    2631   550.8    2635   582.9 2640.88   603.2 2642.77
   631.7 2649.02   648.2 2650.83   660.6 2650.23     702 2671.92   738.8 2685.57
#Mann= 6 ,-1,0
       0      .1       0      70     .06       0   363.8    .045       0
   384.2     .06       0  673.22      .1       0  683.22     .06       0
#XS Ineff= 3 ,-1
     268     313    2610     313     361    2605   385.5     450    2605
Permanent Ineff=
       F       F       F
Bank Sta=363.8,384.2
XS Rating Curve= 0 ,0
Exp/Cntr(USF)=0,0
Exp/Cntr=0.5,0.3

Type RM Length L Ch R = 1 ,4503    ,285.1,300.4,320.4
XS GIS Cut Line= 3
 2224700.1057167 535229.227997982224833.66590351535285.176938562
2225111.51780905 535365.20005956
#Sta/Elev= 30
       0 2681.07    39.1 2665.96    61.1 2654.98    73.8 2650.67    88.7 2643.28
   125.8 2628.08   130.2 2625.33   138.9 2616.92   143.2  2614.5   164.1 2615.21
   169.5 2614.66   180.7 2611.47     214 2609.43   230.7 2609.39   234.8 2608.23
   247.3 2601.34   251.5 2600.01   259.9 2600.31   272.9 2599.51   292.3 2600.05
   305.2 2600.54   313.9 2602.06   326.4 2601.86   330.6  2603.5   347.2 2612.53
   369.8 2629.43   388.2 2641.38   405.7 2654.22   426.3  2666.2     434 2669.56
#Mann= 4 ,-1,0
       0      .1       0  164.81     .06       0   259.9    .045       0
   292.3      .1       0
Bank Sta=259.9,292.3
XS Rating Curve= 0 ,0
Exp/Cntr(USF)=0,0
Exp/Cntr=0.3,0.1

Type RM Length L Ch R = 1 ,4202    ,451.9,447,442.3
XS GIS Cut Line= 3
2224566.07610526535367.9957303142224731.13020352535442.543181454
2224927.16618048535743.206374925
#Sta/Elev= 30
       0 2656.51    41.7  2645.7   116.4  2628.1   158.4 2620.52   177.8  2614.5
   184.3 2609.85     189 2607.83   208.1 2609.07   221.3 2607.85     227 2608.98
   246.3 2606.61   264.7 2606.66   270.2 2604.93   284.5 2597.94   313.2 2596.08
   322.2 2593.61   332.3 2591.51   346.6 2592.27   351.2 2593.96   358.8 2599.42
   368.8 2611.85   373.4 2616.57   386.1 2624.07   403.4  2632.5   451.7 2653.33
   485.1 2669.82   497.9 2674.72     522 2686.93   532.8 2694.29     540 2696.13
#Mann= 5 ,-1,0
       0      .1       0  191.11     .06       0  311.11      .1       0
   322.2    .045       0   351.2      .1       0
Bank Sta=322.2,351.2
XS Rating Curve= 0 ,0
Exp/Cntr=0.3,0.1

Type RM Length L Ch R = 1 ,3755    ,484.3,493,500
XS GIS Cut Line= 3
2224237.79198385535587.138582272  2224539.577066535885.843189628
 2224684.5185564535922.035711789
#Sta/Elev= 30
       0 2661.21    14.4 2657.55    37.1 2643.73    48.4    2641    59.8 2636.08
    93.6 2624.47   110.9 2620.58   141.7 2615.83   156.4 2607.32   179.2 2607.71
   190.5 2613.66   211.6 2611.48     219 2608.59   224.7 2604.45   243.5 2586.75
   260.5 2584.29   273.5  2583.5   287.2 2585.23   305.8 2590.21   317.1 2594.74
   344.1 2596.64   361.1 2606.08   372.5 2610.93   402.9    2619   418.9 2625.41
   429.4 2627.39   454.1 2640.82   520.1 2670.23   537.5 2678.86     574 2700.64
#Mann= 5 ,-1,0
       0      .1       0      80     .06       0     220      .1       0
   260.5    .045       0   287.2      .1       0
Bank Sta=260.5,287.2
XS Rating Curve= 0 ,0
Exp/Cntr=0.3,0.1

Type RM Length L Ch R = 1 ,3262    ,496.6,500.5,514.6
XS GIS Cut Line= 3
2223911.34521101535827.4057108712224056.90170278536119.869456896
2224192.36093793536145.633919054
#Sta/Elev= 30
       0 2634.44    15.4 2628.67    28.8 2621.63    46.7 2614.72    51.1  2612.1
    55.7 2607.28    60.1 2604.72    77.9 2601.91    91.4 2602.91   118.1 2601.64
   122.6 2599.65   127.2 2595.64   131.6 2593.94   140.5 2594.81   157.1 2593.79
   176.2 2580.84   189.6 2579.19   194.1 2577.02   210.8 2572.44   234.3 2571.44
   240.6 2572.73   243.3 2574.13   252.5 2583.68   264.5  2590.7   310.3 2608.52
   338.2 2617.09   395.2 2627.15   427.7 2637.24   452.2 2646.41   464.6 2652.49
#Mann= 4 ,-1,0
       0      .1       0     130     .06       0   210.8    .045       0
   240.6      .1       0
Bank Sta=210.8,240.6
XS Rating Curve= 0 ,0
Exp/Cntr=0.3,0.1

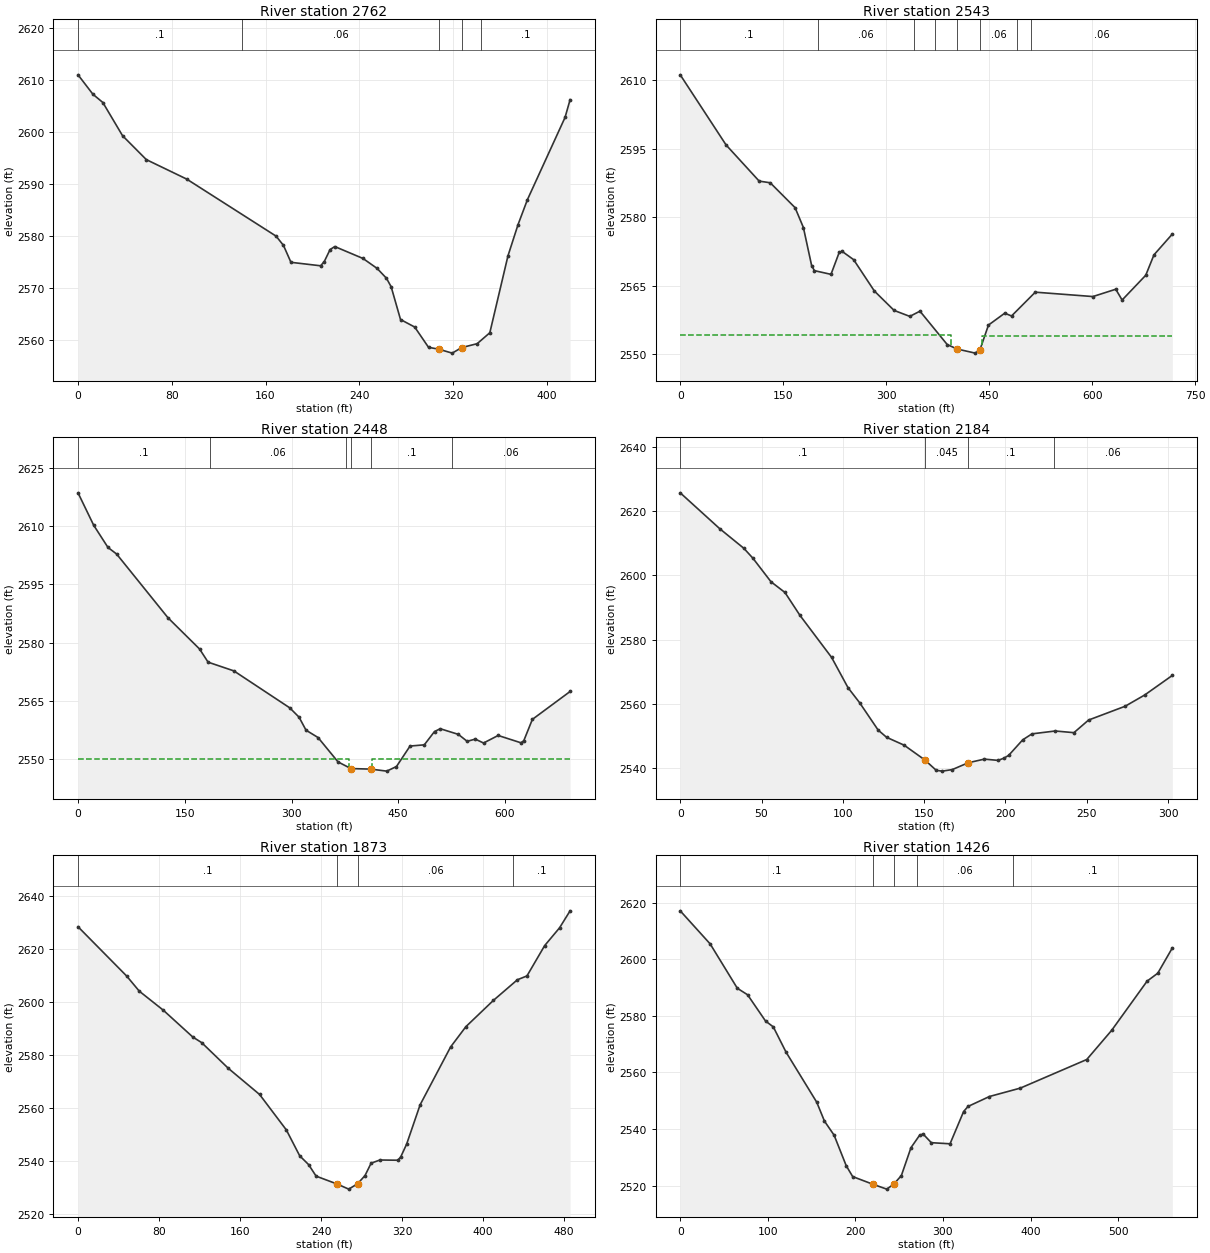
Type RM Length L Ch R = 1 ,2762    ,200.6,218.2,250.5
XS GIS Cut Line= 3
2223582.44340794536005.1063092912223650.23937251536208.373609268
2223635.90575806536413.541571424
#Sta/Elev= 30
       0 2611.04    12.7  2607.3    21.2  2605.7      38  2599.3    58.3 2594.69
    92.8 2590.93     169 2579.94   175.3 2578.16   181.7 2574.89     207 2574.22
   210.1 2575.02   215.1 2577.35   219.1 2577.93   243.2 2575.63   255.2 2573.72
   263.2 2571.82   267.2 2570.18   275.2 2563.86   287.3 2562.41   299.1  2558.5
   307.8 2558.14   319.3 2557.38   327.4 2558.45   340.6  2559.2   351.4 2561.31
   366.9 2576.15   375.5 2582.17   383.5 2586.98   415.6 2602.83   419.9 2606.25
#Mann= 5 ,-1,0
       0      .1       0     140     .06       0   307.8    .045       0
   327.4     .06       0  344.28      .1       0
Bank Sta=307.8,327.4
XS Rating Curve= 0 ,0
Exp/Cntr(USF)=0,0
Exp/Cntr=0.5,0.3

Type RM Length L Ch R = 1 ,2543    ,89.5,95.2,85.5
XS GIS Cut Line= 4
2223551.23715654536034.7749905252223576.01130496536274.258425247
2223242.15016197536516.1013026752223238.61099791536579.806255754
#Sta/Elev= 30
       0  2611.2    66.8 2595.85     115 2587.94   131.1 2587.58   167.3 2582.13
   179.4 2577.79   191.4 2569.47   195.4 2568.35   219.6 2567.54   231.6 2572.35
   235.7 2572.58   252.6 2570.75   282.8 2563.89   311.5 2559.65   334.4 2558.34
   349.2 2559.48   388.9 2552.18   403.6 2551.19   429.8  2550.3   436.7 2551.08
     449 2556.44   472.7 2559.04   482.6 2558.43   517.2 2563.64   601.1 2562.68
   634.4 2564.28   643.7 2561.92   678.1 2567.34   690.1 2571.81   716.8 2576.35
#Mann= 8 ,-1,0
       0      .1       0     200     .06       0  340.76      .1       0
  370.76     .06       0   403.6    .045       0   436.7     .06       0
  490.76      .1       0  510.76     .06       0
#XS Ineff= 2 , 0
          394.35  2554.2  439.02         2554.15
Permanent Ineff=
       F       F
Bank Sta=403.6,436.7
XS Rating Curve= 0 ,0
Exp/Cntr(USF)=0,0
Exp/Cntr=0.5,0.3

Type RM Length L Ch R = 1 ,2448    ,304.5,264.1,229.8
XS GIS Cut Line= 4
2223504.04830241536051.2910894722223522.92384406536236.401167019
2223211.47740678 536460.654399072223205.57880002 536582.16569846
#Sta/Elev= 30
       0 2618.57      22 2610.24    42.1 2604.52    54.2 2602.84   126.5 2586.42
   170.8 2578.41   182.8 2575.02     219 2572.78   297.5 2563.28   310.6 2560.88
   320.4 2557.53   337.3 2555.64   365.4 2549.37   383.5 2547.66   411.3 2547.52
   433.8    2547   447.5 2548.18   466.6 2553.45   486.6 2553.76     501 2557.19
   509.1  2557.9   534.5 2556.45   546.8 2554.67   558.3 2555.23   569.9 2554.23
   590.4 2556.17   622.4 2554.29   626.4 2554.81   638.5 2560.31   691.5 2567.48
#Mann= 6 ,-1,0
       0      .1       0  186.07     .06       0  376.07      .1       0
   383.5    .045       0   411.3      .1       0  526.07     .06       0
#XS Ineff= 2 , 0
          381.41 2550.17  412.56         2550.15
Permanent Ineff=
       F       F
Bank Sta=383.5,411.3
XS Rating Curve= 0 ,0
Exp/Cntr(USF)=0,0
Exp/Cntr=0.5,0.3

Type RM Length L Ch R = 1 ,2184    ,306.6,311.2,313.4
XS GIS Cut Line= 2
2223022.03775187536349.4184726662223198.81899666536595.001066784
#Sta/Elev= 30
       0 2625.63    24.3 2614.48    39.1  2608.4    44.7 2605.31    55.8    2598
    64.4 2594.67    73.6 2587.57    93.1 2574.48   103.2 2565.07   110.3 2560.43
   121.7 2551.92   126.9 2549.67   137.7 2547.22   150.4 2542.64   157.4 2539.42
   161.1 2539.16   167.3 2539.64   177.1 2541.76     187 2542.89   195.4  2542.5
   199.1 2543.19     202 2544.07   210.6 2548.88   216.3 2550.74   230.6 2551.63
   242.1 2551.11   251.1 2555.03   273.6 2559.32   285.6 2562.81   302.6 2568.89
#Mann= 4 ,-1,0
       0      .1       0   150.4    .045       0   177.1      .1       0
     230     .06       0
Bank Sta=150.4,177.1
XS Rating Curve= 0 ,0
Exp/Cntr(USF)=0,0
Exp/Cntr=0.3,0.1

Type RM Length L Ch R = 1 ,1873    ,458.6,446.6,432.6
XS GIS Cut Line= 2
2222775.53071904536442.164006501 2222977.8149017536883.952661443
#Sta/Elev= 30
       0 2628.36      48  2609.8    60.5 2604.08    84.2 2596.91   113.3 2586.81
   122.1 2584.69   148.5 2574.97   179.3 2565.14   205.7 2551.79   218.9 2542.03
   227.7 2538.71   235.1 2534.37   256.2 2531.34   267.3 2529.47   276.1  2531.5
   283.4 2534.59   289.4 2539.24   298.1 2540.45   315.7 2540.36   318.6 2541.56
   324.5 2546.44   337.8 2561.25   367.9 2583.05     383  2590.7   410.1 2600.58
   433.9 2608.39   443.3 2609.82   460.8 2621.26   475.5 2627.96   485.9 2634.36
#Mann= 4 ,-1,0
       0      .1       0   256.2    .045       0   276.1     .06       0
     430      .1       0
Bank Sta=256.2,276.1
XS Rating Curve= 0 ,0
Exp/Cntr(USF)=0,0
Exp/Cntr=0.3,0.1

Type RM Length L Ch R = 1 ,1426    ,459.4,464.7,469.6
XS GIS Cut Line= 3
2222360.21521984536836.0301900082222715.52334101537042.117315308
2222864.48541312537016.678056496
#Sta/Elev= 30
       0 2617.08    34.2 2605.38    65.2 2589.71    76.9 2587.42    97.4 2578.14
   106.3 2576.06   120.8 2567.16   155.9 2549.44   164.7 2542.76   175.7 2537.81
   189.5 2527.04   196.9 2523.17   220.3 2520.43   235.8 2518.74   243.7 2520.46
   252.5 2523.52   263.5  2533.4   273.4  2537.8   277.4 2538.19   286.7 2535.15
   308.1 2534.76   323.6 2546.16   328.6 2547.95   353.1 2551.47   388.4 2554.44
   464.2 2564.54   492.6 2574.83   533.1 2592.23   545.3 2595.04   561.9 2603.96
#Mann= 5 ,-1,0
       0      .1       0   220.3    .045       0   243.7      .1       0
     270     .06       0     380      .1       0
Bank Sta=220.3,243.7
XS Rating Curve= 0 ,0
Exp/Cntr(USF)=0,0
Exp/Cntr=0.3,0.1

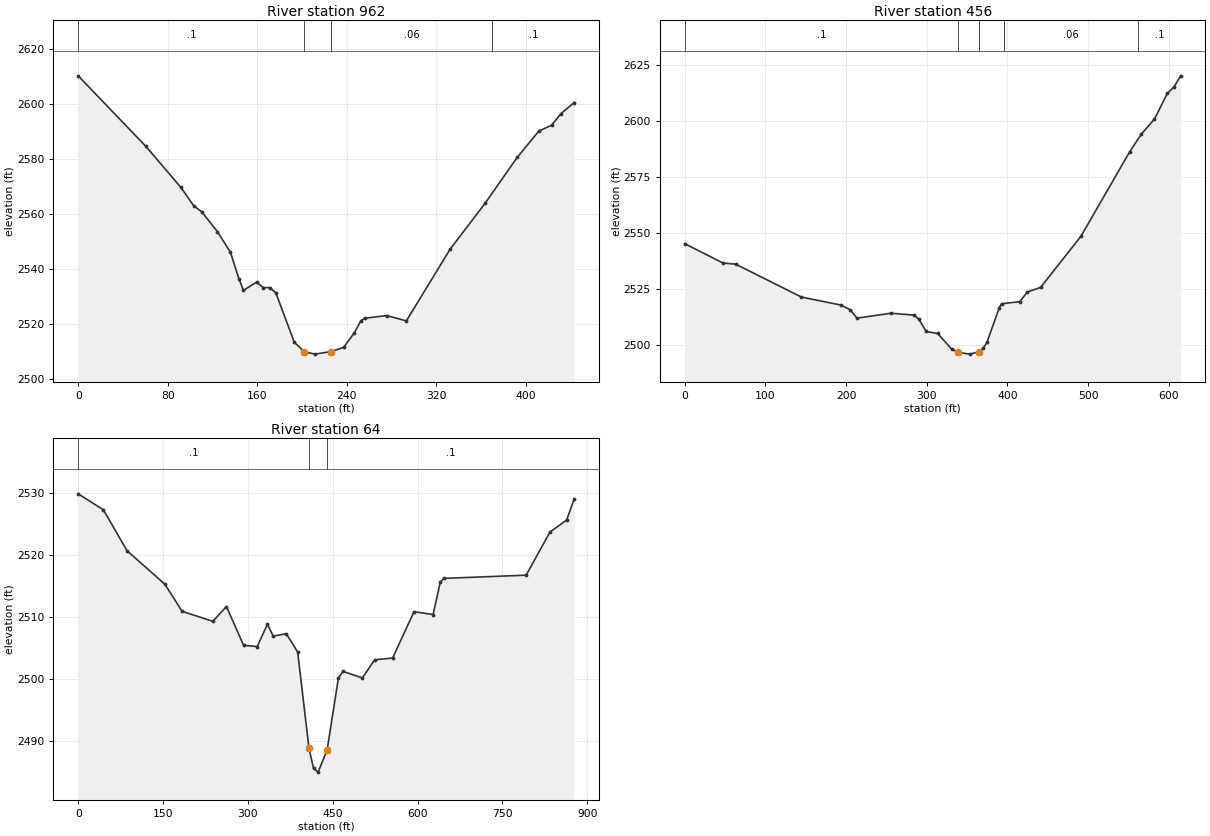
Type RM Length L Ch R = 1 ,962     ,504.9,505.2,505.2
XS GIS Cut Line= 2
2222127.93543953537171.7572022952222449.81003099537476.154440371
#Sta/Elev= 30
       0  2610.2    60.3 2584.63    91.7 2569.67     103 2563.08   110.4 2560.75
   124.3 2553.61     136 2546.09   143.5 2536.52   147.6 2532.22   159.3 2535.25
   165.3 2533.25     171 2533.24   176.5 2531.38     193 2513.42   202.1 2509.91
   211.6 2509.08   226.1 2510.03   237.1 2511.55   246.6  2516.8   252.4 2521.14
   255.8 2522.11   275.7 2523.09   293.1 2521.15   332.2 2547.21   363.4 2563.85
   392.1 2580.54   411.5 2590.15   422.8 2592.24   431.3 2596.49     443  2600.5
#Mann= 4 ,-1,0
       0      .1       0   202.1    .045       0   226.1     .06       0
     370      .1       0
Bank Sta=202.1,226.1
XS Rating Curve= 0 ,0
Exp/Cntr(USF)=0,0
Exp/Cntr=0.3,0.1

Type RM Length L Ch R = 1 ,456     ,373.9,392.7,409.2
XS GIS Cut Line= 4
2221923.15911573537382.504955164  2221840.578621537592.233195752
2222039.82044956537783.6102152882222152.54937887537790.164222807
#Sta/Elev= 30
       0 2545.31    47.5 2536.69    63.1  2536.2   144.7 2521.53   193.7 2517.96
   204.9 2515.92   213.5 2512.13   255.6 2514.33   284.5 2513.49   290.3 2511.63
   299.3  2506.2   313.5  2505.3   330.7 2498.43   338.9 2496.94   353.1 2496.11
   364.4  2497.1   370.1 2498.72   374.6  2501.4   389.9 2516.83   392.7 2518.55
   415.3 2519.49   424.5 2523.75   441.1 2525.85   491.1 2548.62   551.4  2586.2
   566.1  2594.2   582.2 2600.81   598.2 2612.29   606.2    2615   614.6 2620.08
#Mann= 5 ,-1,0
       0      .1       0   338.9    .045       0   364.4      .1       0
   395.4     .06       0  561.67      .1       0
Bank Sta=338.9,364.4
XS Rating Curve= 0 ,0
Exp/Cntr(USF)=0,0
Exp/Cntr=0.3,0.1

Type RM Length L Ch R = 1 ,64      ,,,
XS GIS Cut Line= 4
2221804.88549605 537459.737379762221551.12743296537683.766464753
 2221559.6214267537891.8693114772221872.83744601537995.920734839
#Sta/Elev= 30
       0 2529.89    44.5 2527.31    86.3  2520.7   153.3 2515.28   183.5 2510.92
   237.9 2509.29   262.1 2511.68   292.3 2505.42   316.5 2505.22   334.6 2508.84
   344.7 2506.91   367.9 2507.29     388 2504.33     408 2488.76     416 2485.54
     424 2484.93     440 2488.47     460 2500.12     468 2501.21   502.4 2500.15
   524.1 2503.08   555.8 2503.36   593.7 2510.85   627.4 2510.39     640 2515.58
   646.3 2516.23   791.9 2516.75     834 2523.71   863.5 2525.65   876.8 2529.04
#Mann= 3 ,-1,0
       0      .1       0     408    .045       0     440      .1       0
Bank Sta=408,440
XS Rating Curve= 0 ,0
Exp/Cntr(USF)=0,0
Exp/Cntr=0.3,0.1
LCMann Table=0

Chan Stop Cuts=-1
Use User Specified Reach Order=0
Composite Channel Slope=5